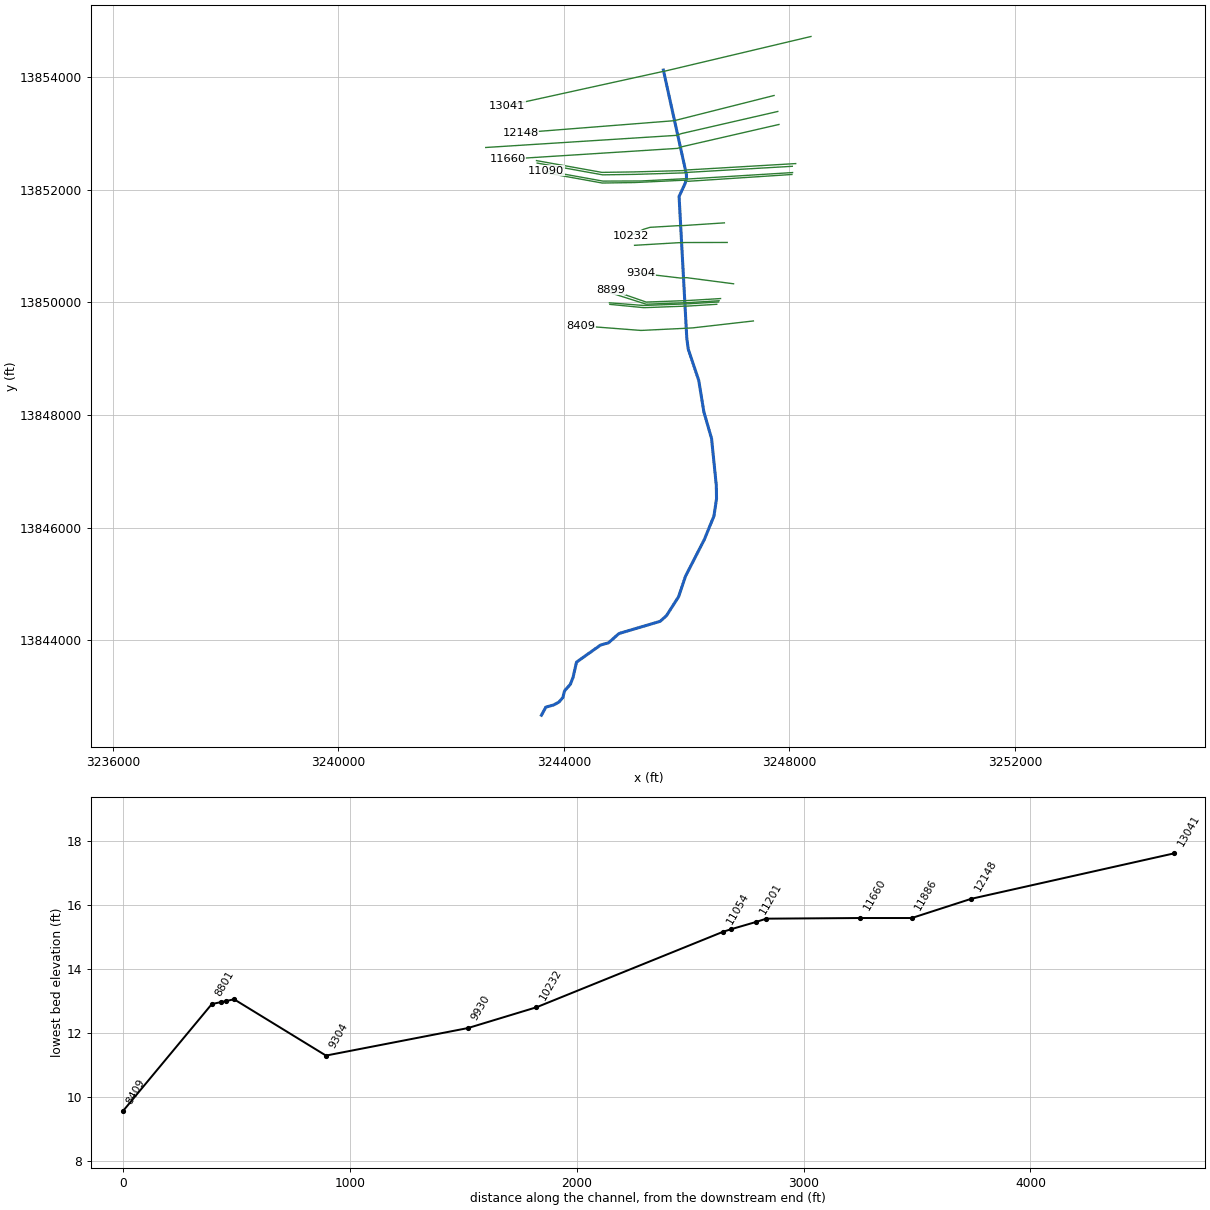
--- O105-00-00.prj (project) ---

Proj Title=O105-00-00
Current Plan=p04
Default Exp/Contr=.3,.1
English Units
Geom File=g02
Flow File=f06
Flow File=f02
Plan File=p02
Plan File=p04
Y Axis Title=Elevation
X Axis Title(PF)=Main Channel Distance
X Axis Title(XS)=Station
BEGIN DESCRIPTION:
Goose Creek Watershed
EF Goose Creek
HCFCD Unit O 105-00-00
(Flood Hazard) Model
10, 2, 1, 0.2% Event
Filename o1050000.prj
Prepared by:  FTN Associates Ltd.   DATE:  May 2003
Reviewed by:     DATE:
STATUS (FINAL RAS)
Normal Depth Calculated between RS 1168 and RS 1839 with inverts -3.42 and -1.67 respectively. Distance between cross sections is 671.73. Normal Depth Calculated to be 0.0026.
Manning's n values adopted from old HEC-2 data.
END DESCRIPTION:
DSS Export Rating Curves= 0
DSS Export Rating Curve Sorted= 0
DSS Export Volume Flow Curves= 0
DXF OffsetX= 0
DXF OffsetY= 0
DXF ScaleX= 1
DXF ScaleY= 10

--- O105-00-00.p04 (plan) ---

Plan Title=Floodway
Version=Version 3.0.1  Mar 2001
Short Identifier=Floodway0607
Geom File=g02
Flow File=f06
Subcritical Flow
K Sum by GR= 0
Std Step Tol= 0.01
Critical Tol= 0.01
Num of Std Step Trials= 20
Max Error Tol= 0.3
Flow Tol Ratio= 0.001
Split Flow NTrial= 30
Split Flow Tol= 0.02
Split Flow Ratio= 0.02
Log Output Level= 0
Friction Slope Method= 1
Unsteady Friction Slope Method= 2
Parabolic Critical Depth
Global Vel Dist= 0 , 0 , 0
Global Log Level= 0
CheckData=True
Encroach Param=-1 ,0,0, 2
Encroach River=O105-00-00
Encroach Reach=EF Goose Creek
Encroach Node=13041
       1  908.02  960.82
Encroach Node=12148
       1    1750    1880
Encroach Node=11886
       1    1750    1885
Encroach Node=11660
       1    1700    1865
Encroach Node=11245
       1    1851    2085
Encroach Node=11201
       1    1835    2070
Encroach Node=11145
       1    1800    2035
Encroach Node=11090
       1    1800    2035
Encroach Node=11054
       1 1867.96 1913.24
Encroach Node=10232
       1     738    1000
Encroach Node=9930
       1     754     865
Encroach Node=9304
       1  858.13  924.82
Encroach Node=8899
       1   616.2   659.1
Encroach Node=8861
       1  588.18  631.08
Encroach Node=8850
       1  584.75  631.08
Encroach Node=8840
       1  588.18  631.08
Encroach Node=8801
       1  545.61  588.51
Encroach Node=8409
       1 1172.11  1224.5
Encroach Node=8366
       1 1626.14 1676.53
Encroach Node=8297
       1 1626.08 1678.47
Encroach Node=8229
       1 1626.08 1678.47
Encroach Node=8182
       1 1617.92 1670.31
Encroach Node=7199
       1 1366.56 1451.93
Encroach Node=6108
       1  974.61 1059.61
Encroach Node=5283
       1  642.71  728.77
Encroach Node=5261
       1  643.18  729.24
Encroach Node=5185
       1  643.18  739.78
Encroach Node=5109
       1  657.04  739.78
Encroach Node=5073
       1  668.04  750.78
Encroach Node=3781
       1   712.5  789.45
Encroach Node=3278
       1  646.73  745.38
Encroach Node=2681
       1  423.02  595.13
Encroach Node=1839
       1  414.64   507.1
Encroach Node=1809
       1   427.3     510
Encroach Node=1752
       1   427.3   517.5
Encroach Node=1694
       1   427.3     510
Encroach Node=1625
       1     400  487.12
Encroach Node=1168
       1  433.11  553.22
Encroach Node=252
       1  358.88  537.01
Encroach Reach=O105-00-00_0003
Encroach Node=13041
       1  908.02  960.82
Encroach Node=12148
       1    1750    1880
Encroach Node=11886
       1    1750    1885
Encroach Node=11660
       1    1700    1865
Encroach Node=11245
       1    1851    2085
Encroach Node=11201
       1    1835    2070
Encroach Node=11145
       1    1800    2035
Encroach Node=11090
       1    1800    2035
Encroach Node=11054
       1 1867.96 1913.24
Encroach Node=10232
       1     738    1000
Encroach Node=9930
       1     754     865
Encroach Node=9304
       1  858.13  924.82
Encroach Node=8899
       1   616.2   659.1
Encroach Node=8861
       1  588.18  631.08
Encroach Node=8850
       1  584.75  631.08
Encroach Node=8840
       1  588.18  631.08
Encroach Node=8801
       1  545.61  588.51
Encroach Node=8409
       1 1172.11  1224.5
Encroach Node=8366
       1 1626.14 1676.53
Encroach Node=8297
       1 1626.08 1678.47
Encroach Node=8229
       1 1626.08 1678.47
Encroach Node=8182
       1 1617.92 1670.31
Encroach Node=7199
       1 1366.56 1451.93
Encroach Node=6108
       1  974.61 1059.61
Encroach Node=5283
       1  642.71  728.77
Encroach Node=5261
       1  643.18  729.24
Encroach Node=5185
       1  643.18  739.78
Encroach Node=5109
       1  657.04  739.78
Encroach Node=5073
       1  668.04  750.78
Encroach Node=3781
       1   712.5  789.45
Encroach Node=3278
       1  646.73  745.38
Encroach Node=2681
       1  423.02  595.13
Encroach Node=1839
       1  414.64   507.1
Encroach Node=1809
       1   427.3     510
Encroach Node=1752
       1   427.3   517.5
Encroach Node=1694
       1   427.3     510
Encroach Node=1625
       1     400  487.12
Encroach Node=1168
       1  433.11  553.22
Encroach Node=252
       1  358.88  537.01
Computation Interval=1HOUR
Output Interval=1HOUR
Run HTab= 0
Run UNet= 0
Run PostProcess= 0
UNET Theta= 1
UNET ZTol= 0.02
UNET ZSATol= 0.1
UNET MxIter= 20
UNET MaxInSteps= 20
UNET DtIC= 0
UNET DtMin= 0
UNET MaxCRTS= 20
UNET WFStab= 2
UNET SFStab= 1
UNET WFX= 1
UNET SFX= 1
UNET Convert EG Bridges=-1
UNET Use Existing IB Tables=-1
Instantaneous Interval=1HOUR
Write IC File= 0
Write Velocity= 0
Write Detailed= 0

--- O105-00-00.p02 (plan) ---

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Plan Title=FEMA Effective June 2007
Short Identifier=FEMAeff0607
Geom File=g02
Flow File=f02

--- O105-00-00.f06 (steady flow) ---

Flow Title=Floodway
Version=Version 3.0.1  Mar 2001
Number of Profiles= 2
Profile Names=1PCT_100yr, 1PCTFloodway_100yrFW
River Rch & RM=O105-00-00,O105-00-00_0003 ,13041
     845     845
River Rch & RM=O105-00-00,O105-00-00_0003 ,12148
     900     900
River Rch & RM=O105-00-00,O105-00-00_0003 ,11886
     950     950
River Rch & RM=O105-00-00,O105-00-00_0003 ,11660
    1051    1051
River Rch & RM=O105-00-00,O105-00-00_0003 ,11245
    1065    1065
River Rch & RM=O105-00-00,O105-00-00_0003 ,11054
    1130    1130
River Rch & RM=O105-00-00,O105-00-00_0003 ,10232
    1149    1149
River Rch & RM=O105-00-00,O105-00-00_0003 ,9930
    1188    1188
River Rch & RM=O105-00-00,O105-00-00_0003 ,9304
    1215    1215
River Rch & RM=O105-00-00,O105-00-00_0003 ,8899
    1247    1247
River Rch & RM=O105-00-00,O105-00-00_0003 ,8409
    1285    1285
River Rch & RM=O105-00-00,O105-00-00_0003 ,8182
    1463    1463
River Rch & RM=O105-00-00,O105-00-00_0003 ,7199
    1690    1690
River Rch & RM=O105-00-00,O105-00-00_0003 ,6108
    1884    1884
River Rch & RM=O105-00-00,O105-00-00_0003 ,5283
    1937    1937
River Rch & RM=O105-00-00,O105-00-00_0003 ,5073
    2297    2297
River Rch & RM=O105-00-00,O105-00-00_0003 ,3781
    2455    2455
River Rch & RM=O105-00-00,O105-00-00_0003 ,3278
    2656    2656
River Rch & RM=O105-00-00,O105-00-00_0003 ,2681
    2968    2968
River Rch & RM=O105-00-00,O105-00-00_0003 ,1839
    3053    3053
River Rch & RM=O105-00-00,O105-00-00_0003 ,1625
    3243    3243
River Rch & RM=O105-00-00,O105-00-00_0003 ,1168
    3660    3660
Boundary for River Rch & Prof#=O105-00-00,O105-00-00_0003 , 1
Up Type= 0
Dn Type= 3
Dn Slope=.0026
Boundary for River Rch & Prof#=O105-00-00,O105-00-00_0003 , 2
Up Type= 0
Dn Type= 3
Dn Slope=.0026
DSS Import GetInterval= 0
DSS Import GetPeak= 0
DSS Import FillOption= 0

--- O105-00-00.f02 (steady flow) ---

Flow Title=FEMA Effective June 2007
Program Version=3.13
Number of Profiles= 4
Profile Names=10PCT_10yr, 2PCT_50yr, 1PCT_100yr, 0.2PCT_500yr
River Rch & RM=O105-00-00,O105-00-00_0003 ,13041
     486     722     845    1207
River Rch & RM=O105-00-00,O105-00-00_0003 ,12148
     517     769     900    1285
River Rch & RM=O105-00-00,O105-00-00_0003 ,11886
     546     812     950    1358
River Rch & RM=O105-00-00,O105-00-00_0003 ,11660
     604     898    1051    1501
River Rch & RM=O105-00-00,O105-00-00_0003 ,11245
     612     910    1065    1521
River Rch & RM=O105-00-00,O105-00-00_0003 ,11054
     650     966    1130    1614
River Rch & RM=O105-00-00,O105-00-00_0003 ,10232
     660     982    1149    1641
River Rch & RM=O105-00-00,O105-00-00_0003 ,9930
     683    1016    1188    1698
River Rch & RM=O105-00-00,O105-00-00_0003 ,9304
     698    1038    1215    1735
River Rch & RM=O105-00-00,O105-00-00_0003 ,8899
     717    1066    1247    1782
River Rch & RM=O105-00-00,O105-00-00_0003 ,8409
     739    1099    1285    1835
River Rch & RM=O105-00-00,O105-00-00_0003 ,8182
     842    1251    1463    2087
River Rch & RM=O105-00-00,O105-00-00_0003 ,7199
     974    1446    1690    2406
River Rch & RM=O105-00-00,O105-00-00_0003 ,6108
    1087    1613    1884    2680
River Rch & RM=O105-00-00,O105-00-00_0003 ,5283
    1118    1658    1937    2755
River Rch & RM=O105-00-00,O105-00-00_0003 ,5073
    1328    1967    2297    3261
River Rch & RM=O105-00-00,O105-00-00_0003 ,3781
    1420    2103    2455    3482
River Rch & RM=O105-00-00,O105-00-00_0003 ,3278
    1538    2276    2656    3764
River Rch & RM=O105-00-00,O105-00-00_0003 ,2681
    1720    2544    2968    4202
River Rch & RM=O105-00-00,O105-00-00_0003 ,1839
    1770    2617    3053    4321
River Rch & RM=O105-00-00,O105-00-00_0003 ,1625
    1881    2780    3243    4587
River Rch & RM=O105-00-00,O105-00-00_0003 ,1168
    2125    3139    3660    5169
Boundary for River Rch & Prof#=O105-00-00,O105-00-00_0003 , 1
Up Type= 0
Dn Type= 3
Dn Slope=0.0026
DSS Import GetInterval= 0
DSS Import GetPeak= 0
DSS Import FillOption= 0

--- O105-00-00.g02 (geometry) ---

Geom Title=O105-00-00 June 2007
Program Version=3.13

River Reach=O105-00-00      ,O105-00-00_0003
Reach XY= 30
     3245764.527    13854118.918     3246172.955    13852269.598
     3246174.708    13852185.458     3246146.662    13852099.566
      3246043.24    13851876.946     3246179.967     13849361.52
     3246206.261    13849166.947     3246392.069    13848613.027
      3246483.22    13848053.849     3246619.884    13847580.556
     3246704.087    13846744.425     3246707.593    13846516.547
     3246662.017    13846208.035     3246490.232    13845789.089
     3246157.747    13845141.358     3246034.475    13844775.907
     3245818.867    13844439.348     3245706.681    13844339.433
     3244977.471    13844123.825     3244791.662    13843959.051
     3244649.676    13843918.734     3244223.719    13843615.481
     3244162.255    13843345.302     3244115.446    13843224.506
     3244011.259    13843105.219      3243981.06    13842987.442
     3243911.602    13842907.415     3243817.985    13842856.076
      3243679.13    13842817.149     3243601.692    13842674.187

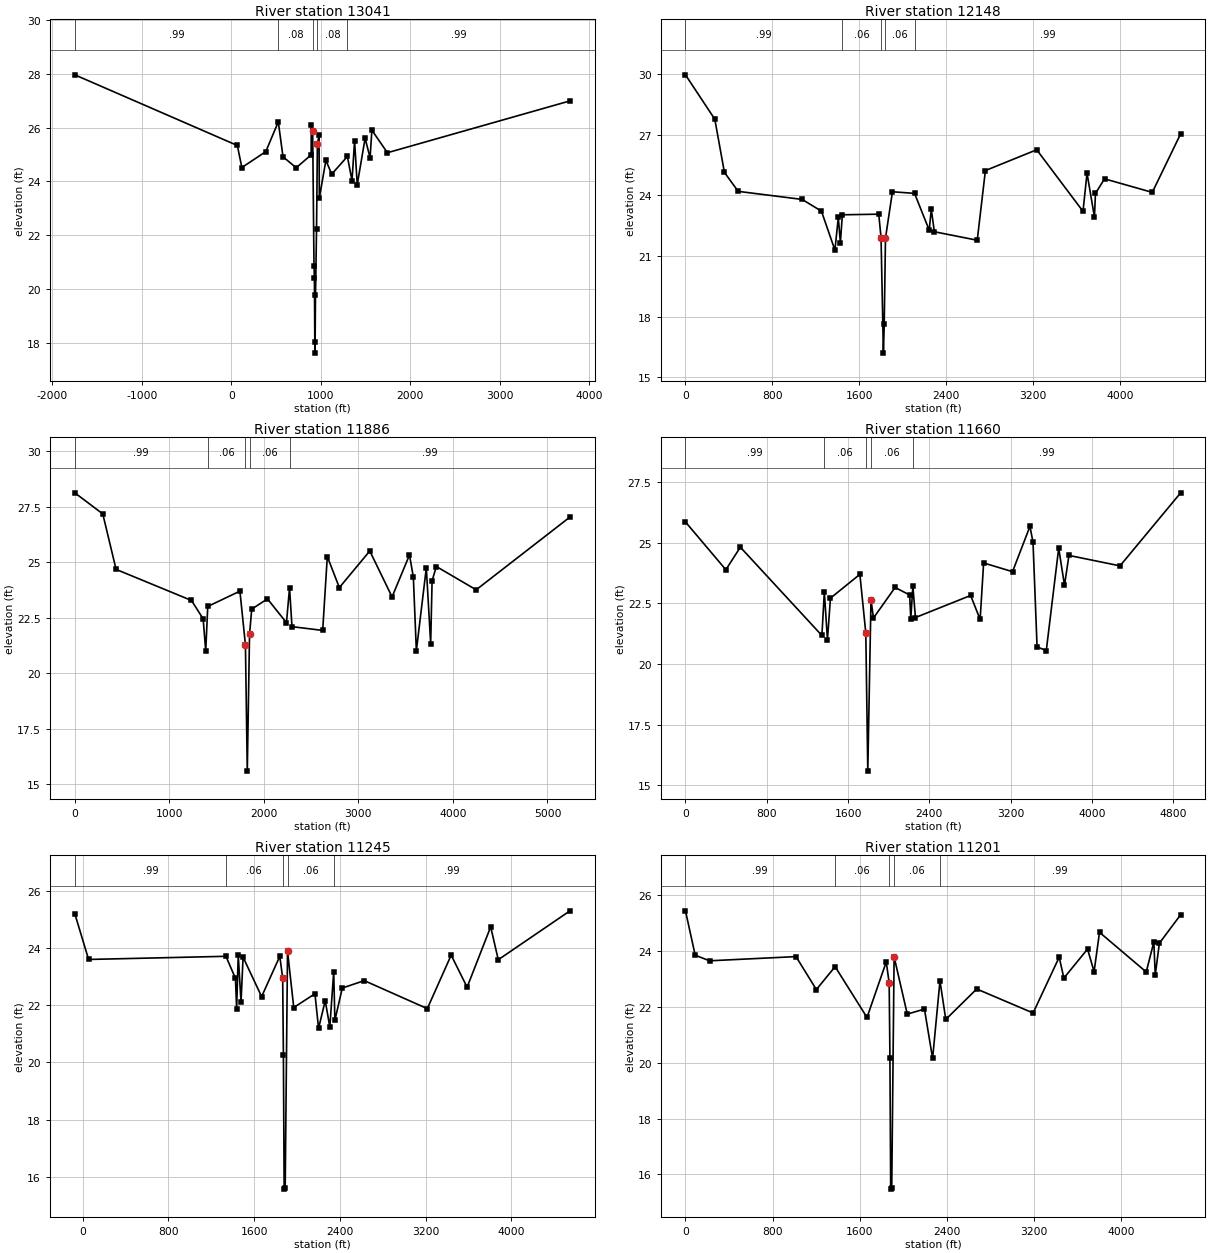
Type RM Length L Ch R = 1 ,13041   ,894.26,893.48,887.8
BEGIN DESCRIPTION:
452v11
Bank Station offset =      4066
ROB and LOB extended above 500yr WSEL based on TIN.
END DESCRIPTION:
XS GIS Cut Line= 6
 3248383.0566228 13854714.671421     3245805.675    13854103.727
     3245731.857    13854088.757     3244941.532    13853914.947
 3244746.199917613853871.9891418 3242988.211056613853485.3683922
#Sta/Elev= 30
   -1750   27.97   66.05   25.34  116.71   24.52  383.94   25.11  523.88   26.22
  576.35   24.92  723.91   24.51  890.85   24.99  892.91    26.1  908.02   25.87
  922.59   20.87  927.33    20.4  931.85   18.02  934.35   17.61  939.48   19.76
  951.24   22.23  960.82    25.4  979.05   25.72  982.41   23.38 1055.93   24.79
 1120.23   24.27 1295.77   24.93 1347.53   24.03 1376.18   25.51 1405.89   23.88
 1494.02   25.61 1549.43   24.88 1569.56   25.91 1743.13   25.07 3783.33      27
#Mann= 5 ,-1 , 0
   -1750     .99       0  523.88     .08       0  908.02    .045       0
  960.82     .08       0 1295.77     .99       0
Bank Sta=908.02,960.82
Exp/Cntr=0.3,0.1

Type RM Length L Ch R = 1 ,12148   ,255.13,261.78,263.55
BEGIN DESCRIPTION:
452v10
Bank Station offset =      3177
LOB and ROB reach lengths > channel reach length due to widening of floodplain.  Set n - 0.06 on near LOB and ROB based on conditions observed from MrSID aerial photos.  Set n = 0.99 locations based on judgement of location of ineffective flow areas using contours developed from LIDAR.
ROB extended above 500yr WSEL based on TIN.
END DESCRIPTION:
XS GIS Cut Line= 5
     3247728.445    13853668.008     3245984.471    13853227.981
     3245939.236    13853219.579     3243453.264    13853023.663
 3243232.767493913853006.2859766
#Sta/Elev= 30
       0   29.97  270.34   27.77  358.63   25.14  485.51    24.2  1074.8    23.8
 1251.84   23.22 1376.28   21.29 1407.22   22.91 1426.47   21.66 1444.56   23.04
 1779.63   23.07 1800.86    21.9 1822.57   16.19 1829.96   17.61 1841.78   21.89
 1905.78   24.18 2109.42    24.1 2244.13   22.28 2263.43   23.31 2291.72    22.2
 2686.49   21.78 2761.72   25.23  3234.1   26.26 3660.41   23.21 3697.32    25.1
 3765.83   22.93 3775.15    24.1  3858.5   24.82 4298.26   24.15  4559.5   27.05
#Mann= 5 ,-1 , 0
       0     .99       0 1444.56     .06       0 1800.86    .045       0
 1841.78     .06       0 2109.42     .99       0
#Block Obstruct= 2 , 0
       0                  3234.1       0   26.26
Bank Sta=1800.86,1841.78
Exp/Cntr=0.3,0.1

Type RM Length L Ch R = 1 ,11886   ,228.49,226.26,232.07
BEGIN DESCRIPTION:
452s8u
Bank Station offset =      3176
LOB and ROB reach lengths > channel reach length
due to widening of floodplain.  Set n = 0.99 locations based on judgement of location of ineffective flow areas using contours developed from LIDAR.
Set n - 0.06 on near LOB and ROB based on conditions observed from MrSID aerial photos.
ROB extended above 500yr WSEL based on TIN.
END DESCRIPTION:
XS GIS Cut Line= 5
     3247794.582    13853384.722     3246087.083     13852992.67
     3245995.008    13852960.688      3243488.65    13852801.262
 3242613.239018213852745.5783063
#Sta/Elev= 30
       0   28.13  295.92   27.18  436.67   24.68  1234.3   23.28 1357.77   22.45
 1384.92      21 1406.26   23.01 1746.58    23.7 1804.87   21.28 1824.34   15.59
 1848.34   21.75 1871.51   22.89 2037.74   23.35 2238.89   22.28 2271.61   23.85
 2297.17    22.1 2622.12   21.93 2670.81   25.26 2798.32   23.86 3120.11   25.51
 3355.89   23.44 3540.22   25.33 3581.05   24.33 3612.83   21.01 3718.22   24.75
 3764.29   21.34 3779.32   24.17 3824.41   24.81 4245.41   23.76    5238   27.04
#Mann= 5 ,-1 , 0
       0     .99       0 1406.26     .06       0 1804.87    .045       0
 1848.34     .06       0 2271.61     .99       0
#Block Obstruct= 2 , 0
       0                 3540.22       0   25.33
Bank Sta=1804.87,1848.34
Exp/Cntr=0.3,0.1

Type RM Length L Ch R = 1 ,11660   ,427.18,414.93,427.22
BEGIN DESCRIPTION:
Copy of 452s8u
Bank Station offset =      3206
LOB and ROB reach lengths > channel reach length due to widening of floodplain.  Set n = 0.99 locations based on judgement of location of ineffective flow areas using contours developed from LIDAR.
ROB extended above 500yr WSEL based on TIN.
0.99 n in ROB is a pond.
END DESCRIPTION:
XS GIS Cut Line= 5
     3247815.558    13853153.986     3246108.059    13852761.934
     3246015.984    13852729.952     3243509.626    13852570.526
 3242999.487062213852538.0767608
#Sta/Elev= 30
       0   25.86  397.47   23.89  539.95   24.82 1342.43   21.18 1366.22   22.97
    1397      21 1426.53   22.72 1716.06    23.7 1774.35   21.28 1793.82   15.59
 1825.32   22.66  1849.4    21.9 2062.65   23.16 2205.57   22.85 2216.86   21.87
 2237.18   23.22 2262.57   21.92 2805.73   22.83 2899.14   21.84 2933.54   24.17
 3217.95   23.81 3389.49   25.68 3419.39   25.02 3459.33   20.71 3550.03   20.56
 3672.09   24.78 3729.14   23.25 3772.94   24.48 4275.36   24.05    4872   27.06
#Mann= 5 ,-1 , 0
       0     .99       0 1366.22     .06       0 1774.35     .04       0
 1825.32     .06       0 2237.18     .99       0
#Block Obstruct= 2 , 0
       0                 3672.09       0   24.78
Bank Sta=1774.35,1825.32
Exp/Cntr=0.3,0.1

Type RM Length L Ch R = 1 ,11245   ,44.45,43.69,45.03
BEGIN DESCRIPTION:
Copy of 452s7d. - xsec 4/4 of Lynchburg Rd.
Bank Station offset =      3119
Invert elevations adjusted.  Set n = 0.99 locations based on judgement of location of ineffective flow areas using contours developed from LIDAR.
ROB high point in 452s7d survey section deleted after checking with TIN
extended LOB 73 ft (-73@25.2ft)
extended ROB 150ft (4548@25.3)
BO is edge of Watershed.
0.99 n in ROB is pond.
END DESCRIPTION:
XS GIS Cut Line= 6
 3248111.552301713852459.9450204      3246190.37    13852347.508
     3246117.554    13852336.131     3245246.514    13852312.492
     3244673.586    13852304.069 3243513.761465913852512.9154583
#Sta/Elev= 30
     -73    25.2    55.7    23.6 1337.33   23.71    1426   22.94 1437.15   21.88
 1452.17   23.75 1478.18    22.1 1497.25   23.68 1670.38    22.3 1839.87   23.71
 1866.79   22.95 1873.58   20.26 1880.59   15.57 1890.19    15.6 1912.07   23.89
  1970.2   21.92 2168.05    22.4  2201.7   21.19 2263.74   22.16 2306.75   21.24
 2343.09   23.17  2353.9   21.47 2423.07    22.6 2628.02   22.86 3216.49   21.88
 3439.17   23.75 3587.86   22.63 3807.88   24.74  3878.6   23.59    4548    25.3
#Mann= 5 ,-1 , 0
     -73     .99       0 1337.33     .06       0 1866.79     .04       0
 1912.07     .06       0 2343.09     .99       0
#Block Obstruct= 2 , 0
       0                 3807.88       0   24.74
Bank Sta=1866.79,1912.07
Exp/Cntr=0.5,0.3

Type RM Length L Ch R = 1 ,11201   ,122.19,111.48,110.04
BEGIN DESCRIPTION:
Copy of 452s7d. - xsec 3/4 of Lynchburg Rd.
Bank Station offset =      3115
Invert elevations adjusted.  Set n = 0.99 locations based on judgement of location of ineffective flow areas using contours developed from LIDAR.
ROB high point in 452s7d survey section deleted after checking with TIN
extended ROB 150ft (4548@25.3ft)
BO is edge of watershed.
END DESCRIPTION:
XS GIS Cut Line= 6
     3248051.696    13852411.986     3246228.419    13852306.089
     3246119.195    13852294.712     3245259.533    13852268.798
     3244686.604    13852260.374 3243526.474340513852469.2765474
#Sta/Elev= 30
       0   25.44   89.36   23.85  221.52   23.65  1015.1    23.8 1202.19   22.62
 1374.47   23.44 1667.31   21.62 1844.13   23.61 1871.05   22.85 1877.84   20.16
 1884.85   15.47 1894.45    15.5 1916.33   23.79 2037.21   21.74 2194.92   21.92
 2269.89   20.15 2337.41   22.93 2390.86   21.55 2674.96   22.64 3192.85   21.78
 3432.58   23.78 3475.25   23.03    3693   24.07  3752.9   23.26 3802.69   24.67
  4231.8   23.25 4301.59   24.32 4314.64   23.14 4352.59   24.28    4548    25.3
#Mann= 5 ,-1 , 0
       0     .99       0 1374.47     .06       0 1871.05     .04       0
 1916.33     .06       0 2337.41     .99       0
#XS Ineff= 2 , 0
       0 1871.05   21.24 1916.33       0    21.5
Permanent Ineff=
       F       F
#Block Obstruct= 2 , 0
       0                 3802.69       0   24.67
Bank Sta=1871.05,1916.33
Exp/Cntr=0.5,0.3

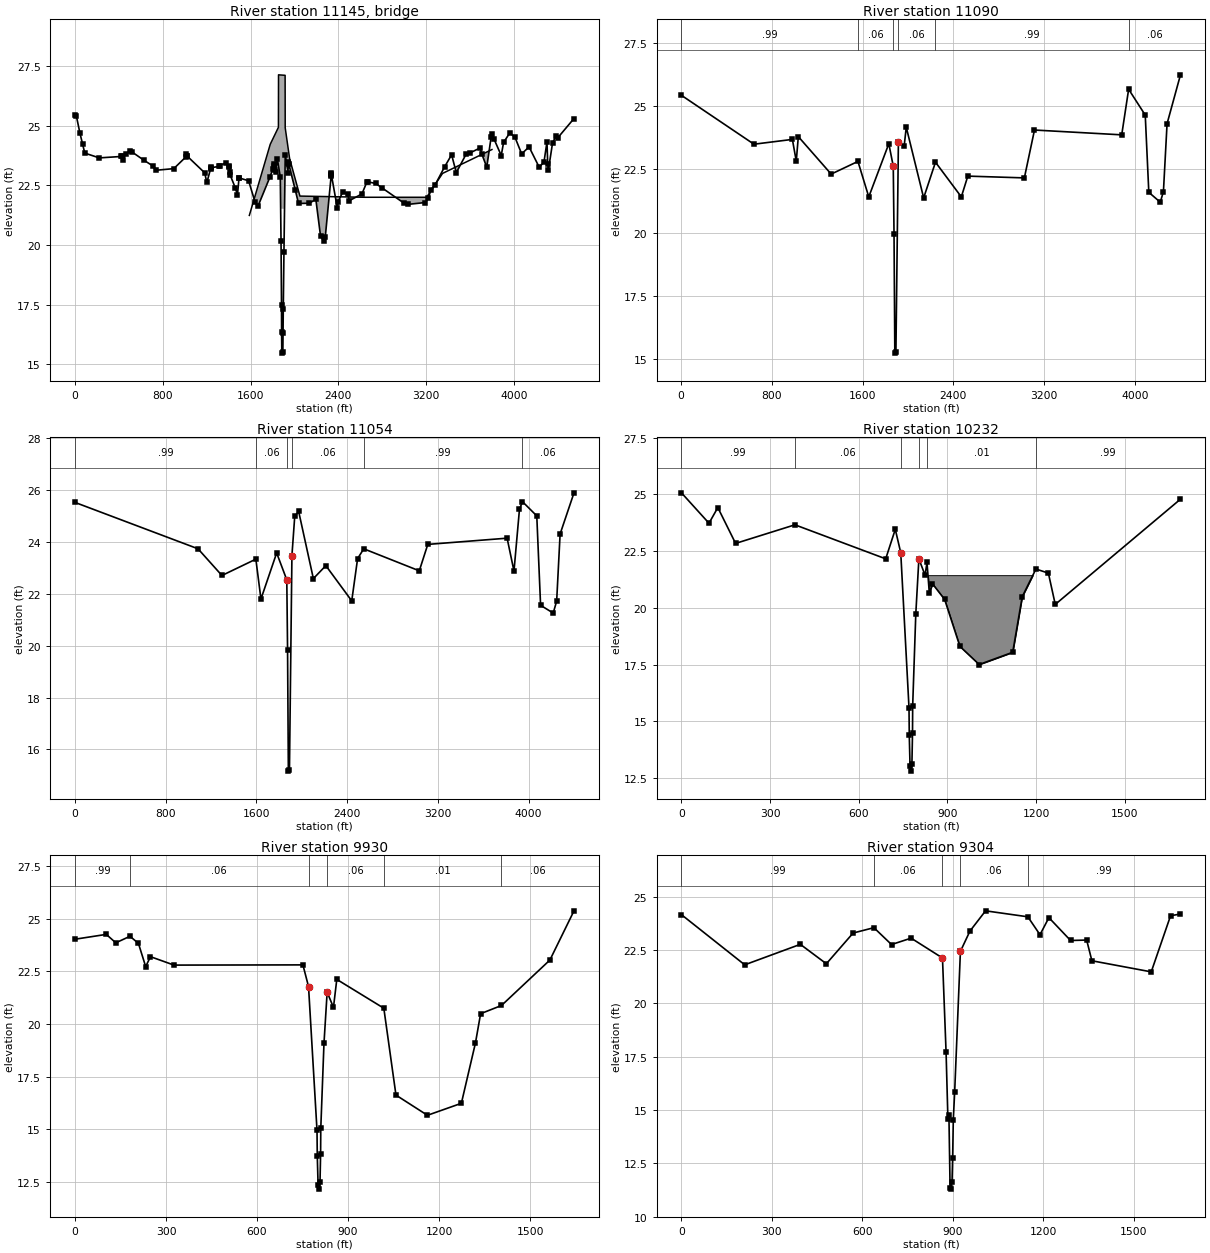
Type RM Length L Ch R = 3 ,11145   ,,,
BEGIN DESCRIPTION:
452s7 -  Lynchburg Rd. (conc. bridge)
roadway extensions beyond survey based on "TIN" elevations
d/s section stationing shifted 4.22' to the right to set encroachment stations at the structure.
END DESCRIPTION:
Bridge Culvert--1,0,-1,-1, 0
Deck Dist Width WeirC Skew NumUp NumDn MinLoCord MaxHiCord MaxSubmerge Is_Ogee
18.25,74.5,2.6,0, 13, 13, , , 0.95, 0, 0,0,,
    1589 1779.43    1854  1854.9    1885  1915.1    1916  1955.8    2050    2640
    3205    3350    3800
   21.24   24.22   24.93   27.13   27.12   27.11   24.91   23.63   22.05      22
      22      23      24
                   21.53   21.53   21.52   21.51   21.51
                        
 1589.22 1779.65 1854.22 1855.12 1885.22 1915.32 1916.22 1956.02 2050.22 2644.22
 3209.22 3354.22 3804.22
   21.24   24.22   24.93   27.13   27.12   27.11   24.91   23.63   22.05      22
      22      23      24
                   21.51   21.51   21.52   21.53   21.53
                        
BR Coef=-1 , 0 , 0 ,, 0 ,,,0.8,0,,0,
WSPro=,,,, 1 ,,,, 0 ,,,, 0 ,,,,-1 ,-1 ,-1 , 0 , 0 , 0 , 0 , 0
BR U #Sta/Elev= 113
       0   25.44   12.27   25.41   43.97   24.71   69.01   24.23   89.36   23.85
  221.52   23.65  423.67   23.71  430.55   23.73  435.71   23.56  466.68   23.83
  505.55   23.94     522   23.89  628.76   23.55  713.91    23.3  734.89   23.13
  900.46    23.2  1010.6   23.69  1015.1    23.8 1017.22   23.75 1018.71   23.74
 1181.01   23.03 1202.19   22.62 1236.03    23.2  1239.8   23.25 1243.25   23.24
 1308.81   23.29 1318.25   23.33 1374.47   23.44 1404.52   23.31 1407.46   23.27
 1409.66   23.06 1413.57   22.94 1462.29   22.38 1480.41   22.09 1495.23   22.82
 1497.26   22.81 1582.55   22.69 1640.82    21.8 1667.31   21.62 1777.78   22.86
 1802.12   23.17 1812.27   23.29 1818.29   23.38 1826.35   23.15 1830.39   23.05
 1844.13   23.61 1871.05   22.85 1877.84   20.16 1882.28   17.48 1883.03   16.37
 1884.85   15.47 1894.45    15.5 1896.26   16.33 1898.37   17.32 1904.44    19.7
 1916.33   23.79 1941.11   23.03 1943.67   23.45 1944.55   23.47 1947.32   23.41
 2008.41   22.29 2037.21   21.74 2137.09   21.75 2194.92   21.92 2238.33   20.36
 2269.89   20.15 2280.82   20.32 2334.51   22.89 2336.41   22.98 2336.78      23
 2337.41   22.93 2390.86   21.55 2397.99   21.81 2442.27   22.24 2484.25   22.12
 2501.27   21.86 2615.06   22.14 2658.62   22.62 2674.96   22.64  2740.2   22.58
 2796.22    22.4 2996.79   21.76  3030.7    21.7 3192.85   21.78 3220.45   21.96
 3243.51   22.32 3281.19   22.51 3369.21   23.28 3432.58   23.78 3475.25   23.03
 3564.93   23.81  3596.9   23.85    3693   24.07 3706.32   23.83  3752.9   23.26
  3792.4   24.51 3802.69   24.67    3818   24.45 3884.93   23.75 3906.16    24.3
 3963.65    24.7 4010.29   24.51 4070.83   23.82 4138.59   24.11  4231.8   23.25
 4274.83   23.49 4301.59   24.32 4308.48   23.41 4314.64   23.14 4352.59   24.28
 4382.02   24.55 4397.86   24.48    4548    25.3
BR U #Mann= 5
       0     .99 1495.23     .06 1871.05     .04 1916.33     .06 2337.41     .99
BR D #Sta/Elev= 101
    4.22   25.42   65.17   25.42  171.62   25.17  466.38   24.31  467.57   24.34
  468.44   24.34     504   24.36  510.45   24.29  514.66   24.28  570.84   23.77
  643.35   23.49  702.82   24.03   754.1   23.85  765.14   23.81  953.01   23.47
  981.92   23.68 1016.15   22.82 1034.21   23.79 1102.81   23.61 1112.75   23.59
 1122.85   23.55 1271.81   22.44 1323.82   22.31 1436.08   22.56 1559.76   22.81
 1610.16   22.16  1638.9   21.97 1655.24   21.41 1661.57   21.54 1831.95   23.51
 1844.13   23.38 1871.05   22.62 1877.84   19.93 1882.28   17.25 1883.03   16.14
 1884.85   15.24 1894.45   15.27 1896.26    16.1 1898.37   17.09 1904.44   19.47
 1916.33   23.56  1967.4   23.43 1985.72    23.6 1995.61    23.6 2076.15    22.2
 2090.86   21.83 2138.92   21.37 2164.24   21.32 2211.01   21.83  2243.1   22.78
 2385.75   21.96 2431.48   22.11 2470.98   21.41 2488.74   21.96 2503.65   21.99
  2511.4   22.09 2528.15   22.23 2582.04   21.98  2588.9   21.99 2624.92   22.01
 2641.53   21.92 2698.99   22.16 2714.68   22.18 2749.83   21.92  2995.3    22.3
 3026.58   22.16 3100.65   23.89 3115.76   24.05 3171.64   24.11 3320.99   23.44
 3369.64   23.69 3373.84   23.73 3390.52   23.86 3396.67   23.75  3409.6   23.86
 3701.61   24.25 3715.09   24.28 3725.56   24.08 3830.77   24.15 3836.37   24.31
 3847.44    24.2 3884.73   23.86 3930.97   25.28  3945.7   25.66 3988.51   25.57
 4025.36   25.38 4047.43   25.34 4092.08   24.64 4107.78   23.25 4123.51   21.59
  4171.8    21.5 4224.63    21.2 4248.94   21.56 4252.34   21.62 4255.56   21.89
 4284.36    24.3 4377.49   26.13 4385.72   26.29  4386.6   26.31 4389.93   26.32
 4402.49   26.23
BR D #Mann= 6
    4.22     .99 1559.76     .06 1871.05     .04 1916.33     .06  2243.1     .99
  3945.7     .06
BC Design=,, 0 ,, 0 ,,,,,,
BC HTab HWMax=25.44

Type RM Length L Ch R = 1 ,11090   ,42.04,35.4,25.91
BEGIN DESCRIPTION:
Copy of 452s7d.  - xsec 2/4 of Lynchburg Rd.
Bank Station offset =      3119
Invert elevations adjusted.  Set n = 0.99 locations based on judgement of location of ineffective flow areas using contours developed from LIDAR.
ROB high point in 452s7d surevy section deleted after checking with TIN
BO is edge of Watershed
END DESCRIPTION:
XS GIS Cut Line= 6
     3248056.881    13852300.946     3246215.012    13852187.493
     3246128.931    13852190.498     3245366.636    13852151.814
      3244691.79    13852149.334     3243679.424    13852331.629
#Sta/Elev= 30
    4.22   25.42  643.35   23.49  981.92   23.68 1016.15   22.82 1034.21   23.79
 1323.82   22.31 1559.76   22.81 1655.24   21.41 1831.95   23.51 1871.05   22.62
 1877.84   19.93 1884.85   15.24 1894.45   15.27 1916.33   23.56  1967.4   23.43
 1985.72   24.16 2138.92   21.37  2243.1   22.78 2470.98   21.41 2528.15   22.23
 3026.58   22.16 3115.76   24.05 3884.73   23.86  3945.7   25.66 4092.08   24.64
 4123.51   21.59 4224.63    21.2 4252.34   21.62 4284.36    24.3 4402.49   26.23
#Mann= 6 ,-1 , 0
    4.22     .99       0 1559.76     .06       0 1871.05     .04       0
 1916.33     .06       0  2243.1     .99       0  3945.7     .06       0
#XS Ineff= 2 , 0
    4.22 1871.05   21.24 1916.33    4.22    21.5
Permanent Ineff=
       F       F
#Block Obstruct= 2 , 0
    4.22                 3944.22    4.22      26
Bank Sta=1871.05,1916.33
Exp/Cntr=0.5,0.3

Type RM Length L Ch R = 1 ,11054   ,810.89,822.26,845.35
BEGIN DESCRIPTION:
452s7d - xsec 1/4 of Lynchburg Rd.
Bank Station offset =      3118
Set n = 0.99 locations based on judgement of location of ineffective flow areas using contours developed from LIDAR.
END DESCRIPTION:
XS GIS Cut Line= 6
     3248045.504    13852266.813     3246203.258    13852146.009
     3246123.445    13852164.838      3245253.34    13852123.625
     3244680.412    13852115.201     3243668.046    13852297.496
#Sta/Elev= 30
       0   25.53 1085.05   23.74  1295.9   22.71 1595.12   23.34 1640.03    21.8
 1778.57   23.58 1867.96   22.54 1874.75   19.85 1881.76   15.16 1891.36   15.19
 1913.24   23.48 1937.96   24.99 1972.72   25.18 2102.27   22.59 2212.38   23.09
 2440.78   21.73 2492.35   23.36 2546.74   23.74 3036.46   22.89 3111.48   23.91
 3811.03   24.15 3871.61   22.88  3919.9   25.26  3946.3   25.56 4072.64   25.01
 4106.22   21.56 4217.45   21.26 4248.02   21.72 4278.33   24.31 4400.92    25.9
#Mann= 6 ,-1 , 0
       0     .99       0 1595.12     .06       0 1867.96     .04       0
 1913.24     .06       0 2546.74     .99       0  3946.3     .06       0
#Block Obstruct= 2 , 0
       0                  3946.3       0   25.55
Bank Sta=1867.96,1913.24
Exp/Cntr=0.5,0.3

Type RM Length L Ch R = 1 ,10232   ,302.1,302.08,302.18
BEGIN DESCRIPTION:
452v9
Bank Station offset =      4222.96
Set n = 0.99 locations based on judgement of location of ineffective flow areas using contours developed from LIDAR.
Blocked area in ROB due to pond.
END DESCRIPTION:
XS GIS Cut Line= 6
     3246846.834    13851408.562     3246116.458     13851360.46
     3246024.482    13851358.626     3245528.254      13851329.1
      3245411.52    13851294.085     3245192.317    13851182.151
#Sta/Elev= 30
       0   25.07   93.17   23.73  123.11   24.42  183.24   22.84  384.07   23.66
  691.34   22.16  723.78   23.46  742.27   22.43  770.22   15.59  771.11   14.38
  773.75   13.01  777.04    12.8  780.08   13.12  782.07   14.47  782.67   15.69
  793.19   19.73  803.64   22.16  824.47   21.44  831.14      22  838.95   20.65
  849.71   21.06  890.81   20.37  942.48    18.3 1007.78    17.5 1121.24   18.04
 1153.47   20.49 1199.83   21.71    1242   21.53 1265.24   20.15 1689.07   24.79
#Mann= 6 ,-1 , 0
       0     .99       0  384.07     .06       0  742.27    .045       0
  803.64     .06       0  831.14     .01       0 1199.83     .99       0
#Block Obstruct= 1 ,-1
  831.14 1199.83   21.44
Bank Sta=742.27,803.64
Exp/Cntr=0.3,0.1

Type RM Length L Ch R = 1 ,9930    ,623.59,625.69,627.62
BEGIN DESCRIPTION:
Copy of 452v9
bank station offset =    4195.37
channel inverts adjusted based on slope between the surveyed locations 452s6u and 452v9
Set n = 0.99 locations based on judgement of location of ineffective flow areas using contours developed from LIDAR.
Note: This cross section is located at the downstream end of the pipes at 452s6. No survey data is available at this location.
Block and n=0.01 used in ROB for pond
END DESCRIPTION:
XS GIS Cut Line= 6
      3246896.97     13851060.89     3246142.161    13851059.522
     3246137.725    13851059.276     3246130.824    13851058.778
     3246038.848    13851056.944     3245253.428     13851010.21
#Sta/Elev= 30
       0   24.03  103.14   24.26  134.54   23.86  181.35   24.17  209.18   23.83
  232.99   22.73  248.91    23.2  326.41    22.8  751.37   22.81  769.86   21.78
  797.81   14.94   798.7   13.73  801.34   12.36  804.63   12.15  807.67   12.47
  809.66   13.82  810.26   15.04  820.78   19.08  831.23   21.51  852.06   20.79
  863.04   22.12 1018.06   20.75 1058.09   16.62 1161.86   15.66  1273.7   16.23
 1320.13    19.1  1337.1   20.49 1405.98   20.88 1565.49   23.04 1644.98   25.38
#Mann= 6 ,-1 , 0
       0     .99       0  181.35     .06       0  769.86    .045       0
  831.23     .06       0 1018.06     .01       0 1405.98     .06       0
#Block Obstruct= 2 , 0
       0                     995       0      21
Bank Sta=769.86,831.23
Exp/Cntr=0.3,0.1

Type RM Length L Ch R = 1 ,9304    ,406.5,405.06,404.56
BEGIN DESCRIPTION:
452v8
Bank Station offset =      4106
Set n = 0.99 locations based on judgement of location of ineffective flow areas using contours developed from LIDAR.
END DESCRIPTION:
XS GIS Cut Line= 4
     3247009.541    13850327.762     3246174.082    13850436.804
     3246067.472    13850429.487     3245367.354    13850511.981
#Sta/Elev= 30
       0   24.15  209.71    21.8  394.13   22.76  480.35   21.85  569.14   23.29
  638.01   23.54  696.41   22.75  761.41   23.05  865.36   22.12  877.29   17.71
  883.37   14.58  886.74   14.75  890.56   11.35   893.6   11.29  896.95   11.62
  899.05   12.73  901.23   14.54  905.81   15.85  924.82   22.43  956.39   23.38
 1008.21   24.33  1148.4   24.05 1188.66   23.21 1218.18   24.01 1290.05   22.94
  1343.4   22.96 1360.72   21.99 1557.48   21.47 1621.57    24.1 1654.37   24.18
#Mann= 5 ,-1 , 0
       0     .99       0  638.01     .06       0  865.36     .04       0
  924.82     .06       0  1148.4     .99       0
Bank Sta=865.36,924.82
Exp/Cntr=0.3,0.1

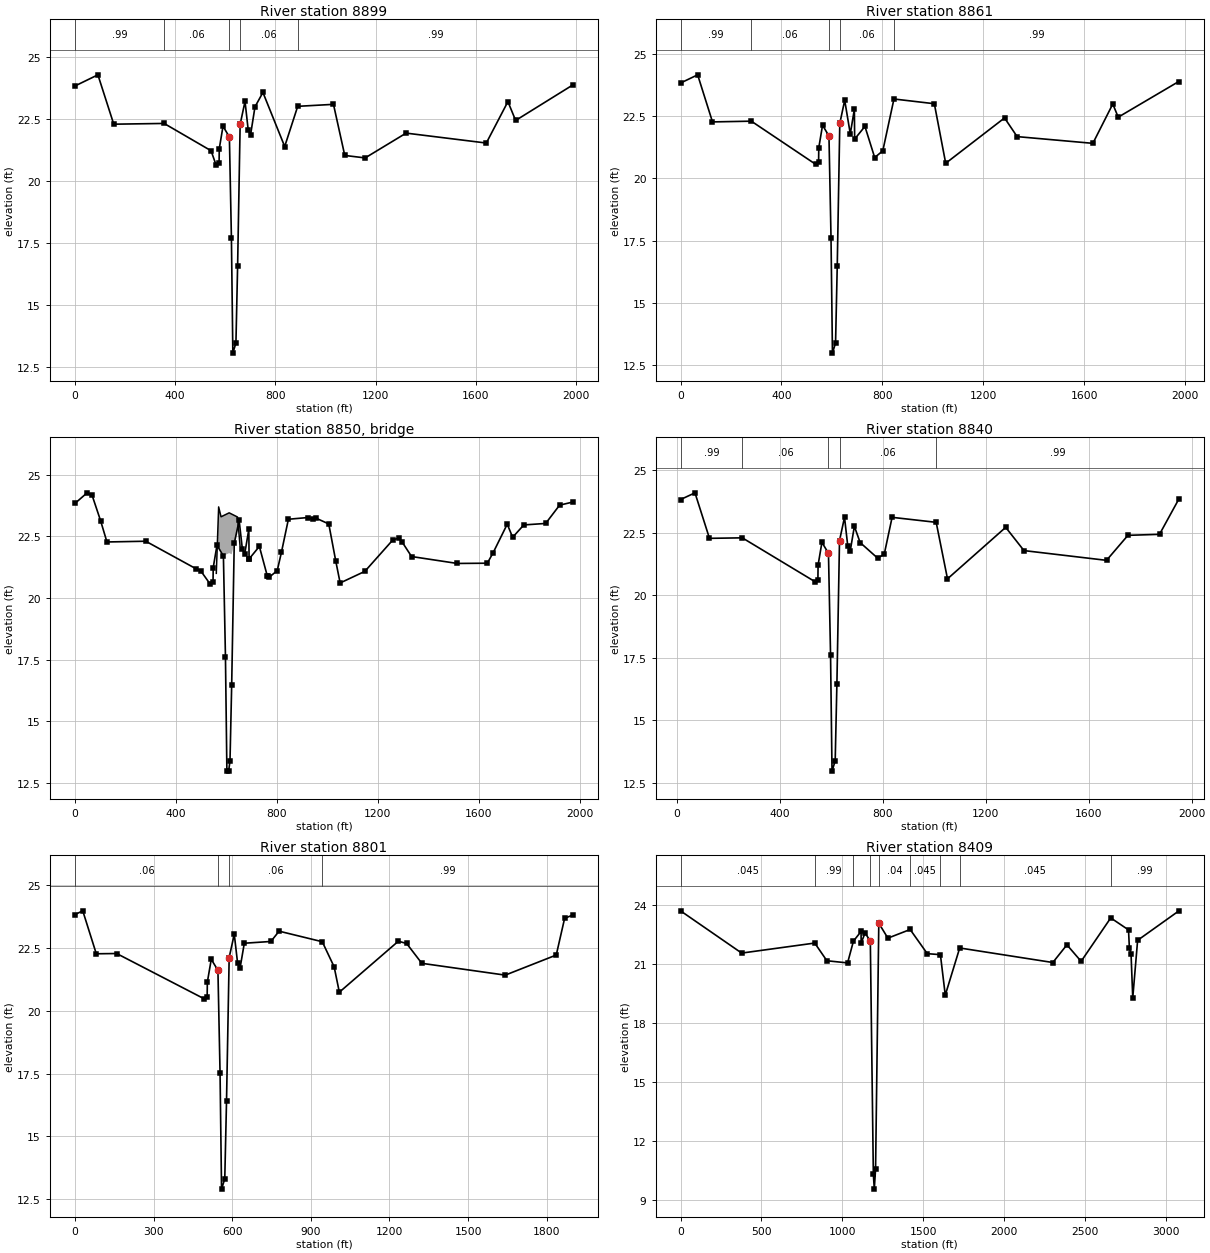
Type RM Length L Ch R = 1 ,8899    ,37.6,37.65,37.62
BEGIN DESCRIPTION:
452s5u -  xsec 4/4 of wooden bridge south of Baker Rd.
Bank Station offset =      4363
Set n = 0.99 locations based on judgement of location of ineffective flow areas using contours developed from LIDAR.
END DESCRIPTION:
XS GIS Cut Line= 5
     3246779.119    13850065.692     3246210.452    13850031.269
     3246070.984    13850026.062     3245459.391    13850003.294
     3244830.035    13850222.493
#Sta/Elev= 30
       0   23.82    91.6   24.27  154.78   22.28  355.78   22.31  543.04   21.21
  563.27   20.63  575.11   20.71  575.81   21.29  590.77    22.2   616.2   21.76
  624.29   17.69  629.99   13.05   642.3   13.46  648.98   16.55   659.1   22.27
  678.55    23.2  691.12   22.06  700.66   21.85  718.33   22.98  749.98   23.56
  836.85   21.38  888.76      23  1031.5   23.08 1076.53   21.02 1157.89   20.92
 1321.29   21.92 1641.32   21.52 1727.52   23.19 1758.25   22.43 1987.73   23.87
#Mann= 5 ,-1 , 0
       0     .99       0  355.78     .06       0   616.2     .04       0
   659.1     .06       0  888.76     .99       0
Bank Sta=616.2,659.1
Exp/Cntr=0.5,0.3

Type RM Length L Ch R = 1 ,8861    ,21,21.02,21.01
BEGIN DESCRIPTION:
Copy of 452s5u - xsec 3/4 of wooden brige south of Baker Rd.
Bank Station offset =      4391
Set n = 0.99 locations based on judgement of location of ineffective flow areas using contours developed from LIDAR.
END DESCRIPTION:
XS GIS Cut Line= 5
     3246753.279    13850026.932     3246212.796    13849993.768
     3246073.328    13849988.561     3245459.313    13849965.703
     3244813.023    13850171.458
#Sta/Elev= 30
       0   23.83   67.92   24.16  126.71   22.27   280.6    22.3  535.25   20.57
  547.09   20.65  547.79   21.23  562.75   22.14  588.18    21.7  596.27   17.63
  601.97   12.99  614.28    13.4  620.96   16.49  631.08   22.21  650.53   23.14
  672.64   21.79  688.84   22.78   689.9   21.58   730.6   22.09  769.31   20.84
  801.44   21.11  845.64   23.19 1005.63      23 1050.66   20.61 1283.81   22.43
 1333.65   21.68 1633.72   21.41 1712.66   22.99 1734.11   22.46 1973.76   23.89
#Mann= 5 ,-1 , 0
       0     .99       0   280.6     .06       0  588.18     .04       0
  631.08     .06       0  845.64     .99       0
#XS Ineff= 2 , 0
       0  588.18      21  631.08       0      21
Permanent Ineff=
       F       F
Bank Sta=588.18,631.08
Exp/Cntr=0.5,0.3

Type RM Length L Ch R = 3 ,8850    ,,,
BEGIN DESCRIPTION:
452s5 - Private Drive (So of Baker Rd)
(Wooden Bridge)
d/s section stationing shifted 13.07' to the right to set encroachment stations at the structure.
END DESCRIPTION:
Bridge Culvert--1,0,-1,-1, 0
Deck Dist Width WeirC Skew NumUp NumDn MinLoCord MaxHiCord MaxSubmerge Is_Ogee
8.5,4,2.6,0, 6, 6, , , 0.95, 0, 0,0,,
     560  569.31  578.82     611  644.13  654.16
      21   23.69   23.29   23.45   23.28   22.11
           22.06   21.66   21.82   21.65   20.48
  553.07  562.38  571.89  604.07   677.2  687.23
      21   23.69   23.29   23.45   23.28   22.11
           22.06   21.66   21.82   21.65   20.48
BR Coef=-1 , 0 , 0 ,, 0 ,,,0.8,0,,0,
WSPro=,,,, 1 ,,,, 0 ,,,, 0 ,,,,-1 ,-1 ,-1 , 0 , 0 , 0 , 0 , 0
BR U #Sta/Elev= 52
       0   23.83   48.08   24.26   67.92   24.16  101.61   23.13  126.71   22.27
   280.6    22.3   478.8   21.19  497.69   21.11  535.25   20.57  547.09   20.65
  547.79   21.23  562.75   22.14  588.18    21.7  596.27   17.63  601.97   12.99
  608.87      13  614.28    13.4  620.96   16.49  631.08   22.21  650.53   23.14
   663.1      22  672.64   21.79  688.84   22.78   689.9   21.58  691.39    21.6
   730.6   22.09  762.16   20.89  764.31   20.89  769.31   20.84  801.44   21.11
  818.04   21.85  845.64   23.19  923.55   23.26  943.39   23.18  953.88   23.24
 1005.63      23 1033.06   21.51 1050.66   20.61  1148.6   21.08 1259.24   22.35
 1283.81   22.43 1295.51   22.28 1333.65   21.68  1514.7    21.4 1633.72   21.41
 1656.13   21.82 1712.66   22.99 1734.11   22.46 1778.34   22.96 1864.89   23.02
 1920.11   23.76 1973.76   23.89
BR U #Mann= 5
       0     .99   280.6     .06  588.18    .035  631.08     .06  845.64     .99
BR D #Sta/Elev= 48
   13.07   23.82   53.18   24.18   69.27   24.09   96.61   23.26  125.62   22.27
  253.24   22.29  417.29   21.38  507.13   20.99  535.25   20.54  547.09   20.62
  547.79    21.2  562.75   22.11  588.18   21.67  596.27    17.6  601.97   12.96
  608.87   12.97  614.28   13.37  620.96   16.46  631.08   22.18  650.53   23.11
   663.1   21.97  672.64   21.76  688.84   22.75  711.32    22.1  735.59   21.77
  750.79   21.77  779.08   21.48  804.86   21.63  835.47   23.11  895.33   23.17
  945.73   23.17 1004.94   22.95 1006.82   22.91 1050.81   20.65 1126.55   21.02
 1273.74    22.7 1277.03   22.71 1341.04   21.88 1348.01   21.78 1588.82   21.57
 1668.92   21.39 1711.55   22.13  1752.1   22.39 1808.33   22.44 1874.86   22.43
 1898.47   22.72    1933   23.75 1949.45   23.83
BR D #Mann= 5
   13.07     .99  253.24     .06  588.18    .035  631.08     .06 1006.82     .99
BC Design=,, 0 ,, 0 ,,,,,,
BC HTab HWMax=24.26

Type RM Length L Ch R = 1 ,8840    ,39.36,39.4,39.38
BEGIN DESCRIPTION:
Copy of 452s5u - xsec 2/4 of wooden brige south of Baker Rd.
Bank Station offset =      4404
Set n = 0.99 locations based on judgement of location of ineffective flow areas using contours developed from LIDAR.
END DESCRIPTION:
XS GIS Cut Line= 5
     3246740.359    13850005.398       3246216.8    13849972.927
     3246077.332     13849967.72     3245413.949    13849943.024
     3244807.353    13849990.001
#Sta/Elev= 30
   13.07   23.82   69.27   24.09  125.62   22.27  253.24   22.29  535.25   20.54
  547.09   20.62  547.79    21.2  562.75   22.11  588.18   21.67  596.27    17.6
  601.97   12.96  614.28   13.37  620.96   16.46  631.08   22.18  650.53   23.11
   663.1   21.97  672.64   21.76  688.84   22.75  711.32    22.1  779.08   21.48
  804.86   21.63  835.47   23.11 1006.82   22.91 1050.81   20.65 1277.03   22.71
 1348.01   21.78 1668.92   21.39  1752.1   22.39 1874.86   22.43 1949.45   23.83
#Mann= 5 ,-1 , 0
   13.07     .99       0  253.24     .06       0  588.18     .04       0
  631.08     .06       0 1006.82     .99       0
#XS Ineff= 2 , 0
   13.07  588.18      21  631.08   13.07      21
Permanent Ineff=
       F       F
Bank Sta=588.18,631.08
Exp/Cntr=0.5,0.3

Type RM Length L Ch R = 1 ,8801    ,394.95,392.22,393.23
BEGIN DESCRIPTION:
Copy of 452s5u - xsec 1/4 of wooden brige south of baker Rd.
Bank Station offset =      4434
END DESCRIPTION:
XS GIS Cut Line= 5
     3246711.647    13849963.766     3246218.656    13849933.644
     3246079.187    13849928.438     3245419.599    13849903.882
     3244814.863    13849962.538
#Sta/Elev= 30
       0   23.83   29.79   23.98   81.44   22.27  159.19   22.28  492.68   20.48
  504.52   20.56  505.22   21.14  520.18   22.05  545.61   21.61   553.7   17.54
   559.4    12.9  571.71   13.31  578.39    16.4  588.51   22.12  607.96   23.05
  620.53   21.91  630.07    21.7  646.27   22.69  747.74   22.76  778.99   23.17
  943.74   22.75  989.12   21.75 1008.94   20.74  1234.1   22.77 1265.66   22.68
 1323.68   21.89 1642.01   21.42 1836.67   22.22 1868.58   23.68  1901.1   23.82
#Mann= 4 ,-1 , 0
       0     .06       0  545.61     .04       0  588.51     .06       0
  943.74     .99       0
Bank Sta=545.61,588.51
Exp/Cntr=0.3,0.1

Type RM Length L Ch R = 1 ,8409    ,42.98,42.97,43
BEGIN DESCRIPTION:
452s4u - xsec 4/4 of Baker Rd.
Bank Station offset =      3803
Manning's n decreased on immediate channel banks to represent protective rocks - but not as low as FIS study due to PMT directive regarding n in maintained channels.
END DESCRIPTION:
XS GIS Cut Line= 5
     3247361.219     13849668.42     3246285.247    13849545.531
     3246095.218    13849535.295     3245366.397    13849500.029
     3244296.111    13849582.369
#Sta/Elev= 30
       0   23.71  377.73   21.56  828.89   22.07  903.89   21.17  1031.7   21.06
 1067.98   22.17 1114.98   22.66 1115.39   22.08 1139.88   22.58 1172.11   22.17
 1190.83   10.31  1196.6    9.55 1204.53   10.58  1224.5   23.08 1280.56   22.32
 1418.01   22.76 1523.99   21.53 1604.89   21.48 1634.93   19.42 1724.01   21.82
 2299.04   21.08 2386.14   21.98 2473.89   21.14 2656.77   23.35 2766.54   22.74
  2771.9   21.81 2782.13   21.52 2792.68   19.28 2822.77   22.21 3076.39    23.7
#Mann= 9 ,-1 , 0
       0    .045       0  828.89     .99       0 1067.98     .04       0
 1172.11    .035       0  1224.5     .04       0 1418.01    .045       0
 1604.89     .99       0 1724.01    .045       0 2656.77     .99       0
Bank Sta=1172.11,1224.5
Exp/Cntr=0.5,0.3