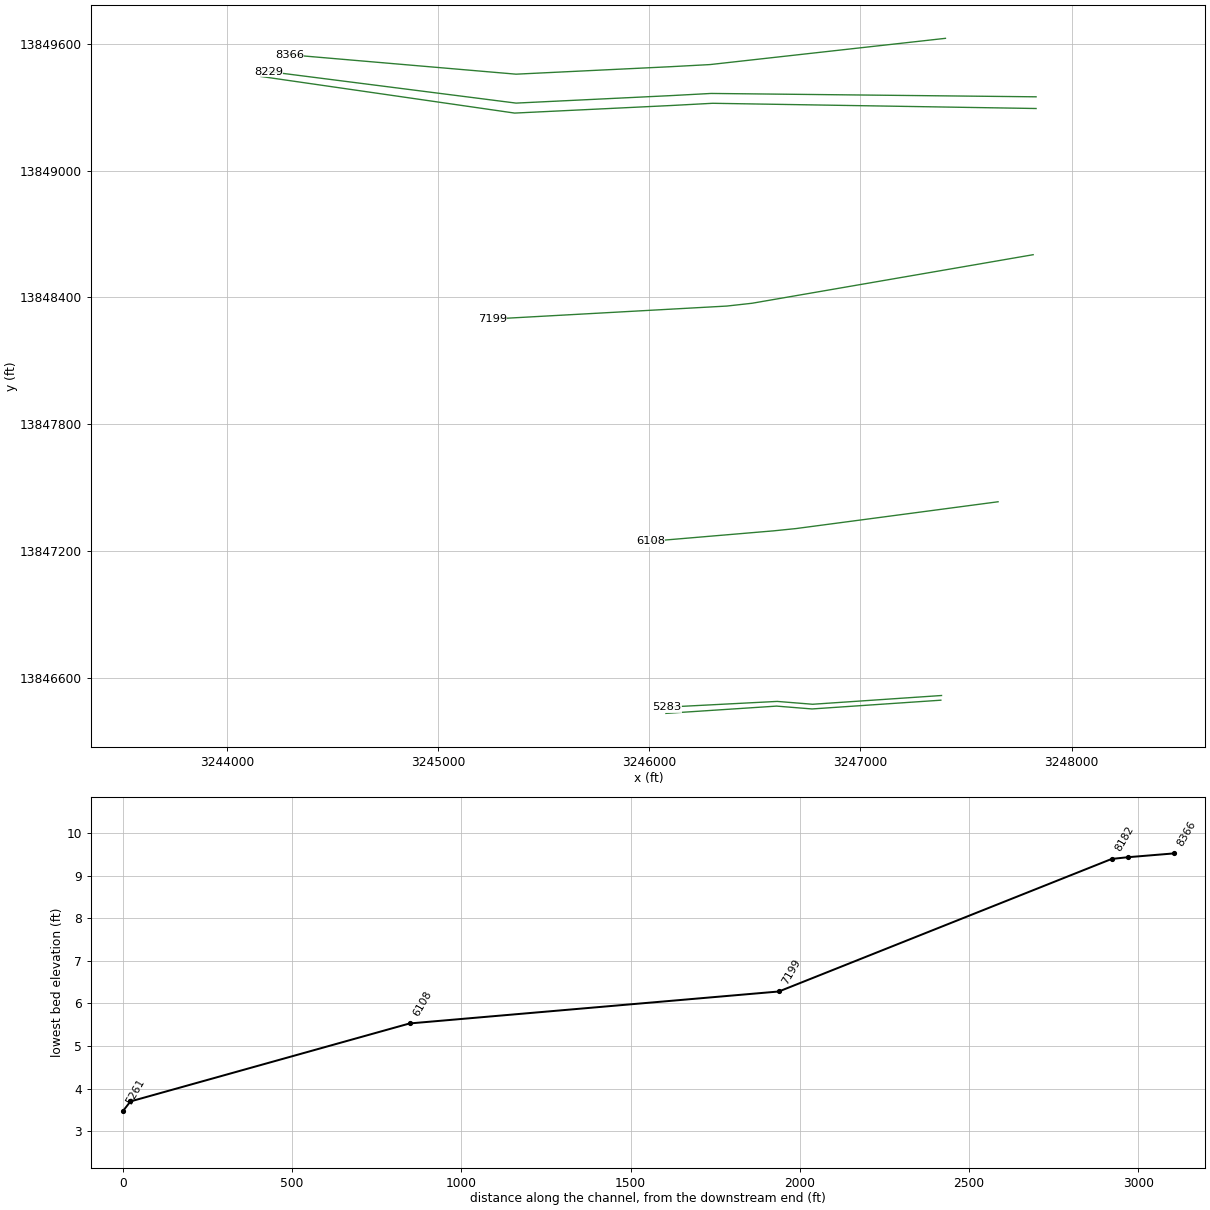
HEC-RAS study O105-00-00.prj: O105-00-00

--- O105-00-00.g02 (geometry) --- (continued)

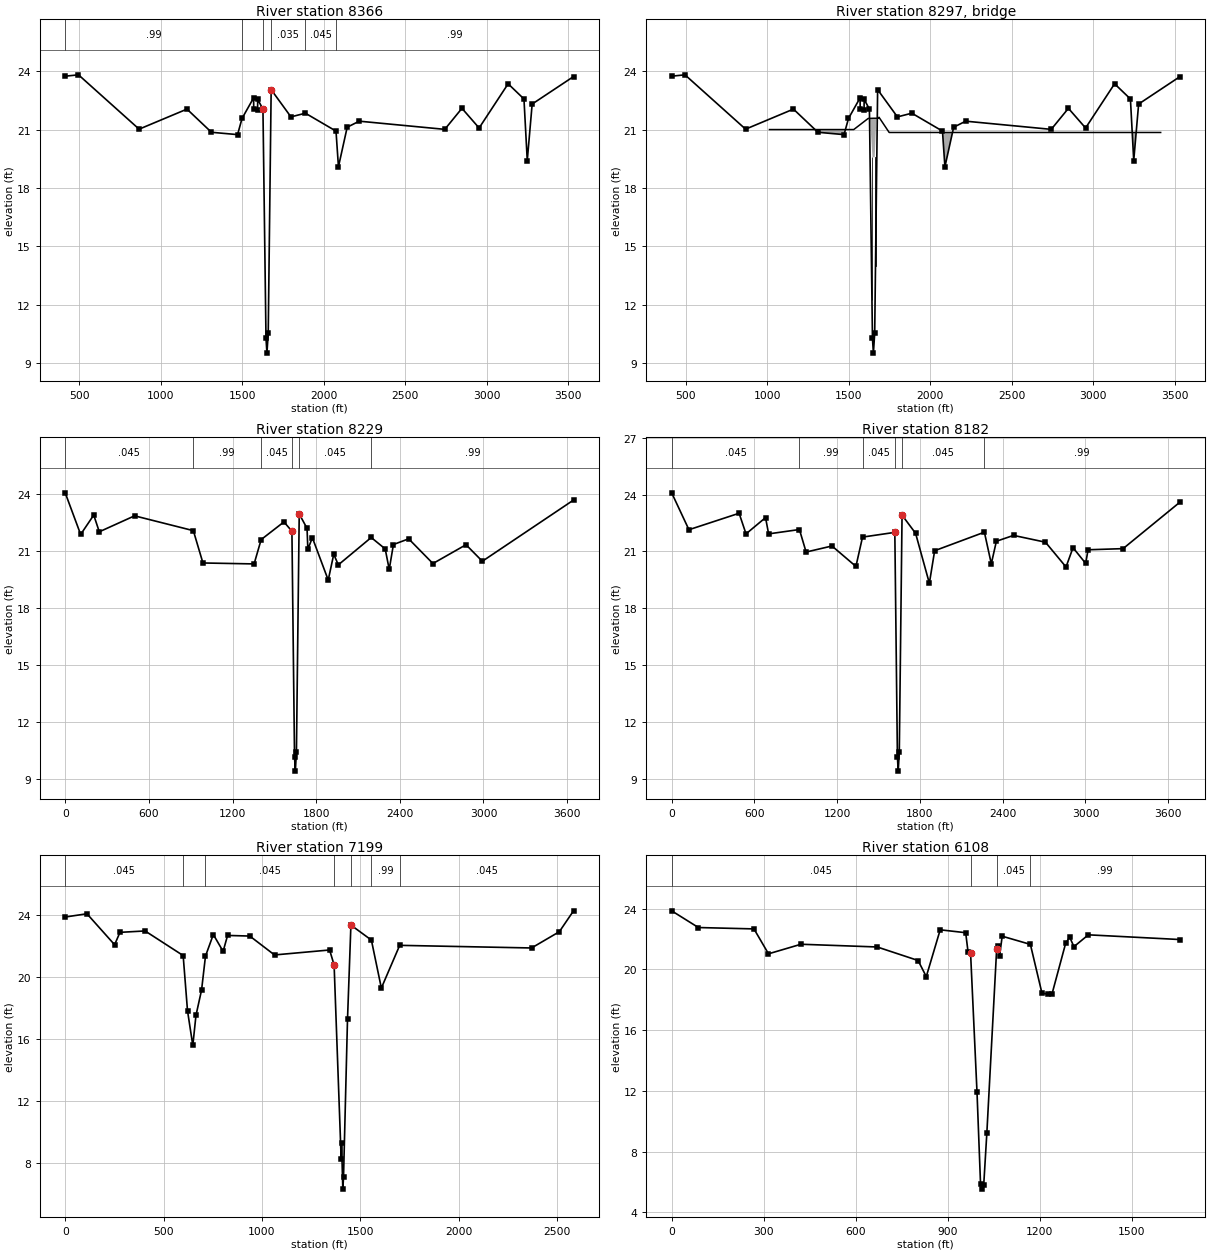
Type RM Length L Ch R = 1 ,8366    ,136.87,136.79,136.95
BEGIN DESCRIPTION:
Copy of 452s4u - xsec 3/4 of Baker Rd.
Bank Station offset =      3762
Manning's n decreased on immediate channel banks to represent protective rocks but not as low as FIS study due to PMT directive regarding n in maintained channels.
END DESCRIPTION:
XS GIS Cut Line= 5
     3247402.751    13849626.888     3246288.204    13849502.659
     3246098.175    13849492.424       3245369.7    13849457.174
     3244296.111    13849549.232
#Sta/Elev= 30
     413   23.74  494.53   23.81  866.47   21.02 1160.04   22.05 1310.17   20.86
 1470.48   20.74  1497.8   21.57 1569.01   22.63 1569.42   22.05 1593.19   21.98
 1593.91   22.55 1626.14   22.05 1644.86   10.28 1650.63    9.52 1658.56   10.55
 1676.53   23.05 1797.93   21.65 1886.54   21.84 2074.35   20.92 2089.37   19.09
 2143.01   21.12 2216.94   21.43 2741.59   21.01 2846.99   22.09 2952.33   21.08
  3130.3   23.35 3227.45   22.57  3247.7   19.41 3277.81   22.31 3531.61   23.72
#Mann= 6 ,-1 , 0
     413     .99       0  1497.8    .035       0 1626.14    .015       0
 1676.53    .035       0 1886.54    .045       0 2074.35     .99       0
#XS Ineff= 2 , 0
       0  1618.5   20.85 1685.12       0   20.85
Permanent Ineff=
       F       F
Bank Sta=1626.14,1676.53
Exp/Cntr=0.5,0.3

Type RM Length L Ch R = 3 ,8297    ,,,
BEGIN DESCRIPTION:
452s4 - Baker Rd. (conc Bridge)
END DESCRIPTION:
Bridge Culvert--1,0,-1,-1, 0
Deck Dist Width WeirC Skew NumUp NumDn MinLoCord MaxHiCord MaxSubmerge Is_Ogee
25,86,2.6,0, 9, 9, , , 0.95, 0, 0,0,,
    1013 1530.06  1618.5 1619.23    1651  1683.5 1685.12 1747.44    3413
      21      21   21.57   21.57   21.58   21.58   21.63   20.85   20.85
                   19.57   19.57   19.58   19.58   19.63
     600 1530.06  1618.5 1619.23    1651  1683.5 1685.12 1747.44    3200
      21      21   21.57   21.57   21.58   21.63   21.63   20.85   20.85
              19   19.57   19.57   19.58   19.63   19.63   18.85
Pier Skew, UpSta & Num, DnSta & Num=  ,1641.7, 4 ,1641.7, 4 , 3 , 3 , 0 ,,
    1.35    1.35     2.3     2.3
       5   17.33   17.33   19.63
    1.35    1.35     2.3     2.3
       5   17.33   17.33   19.63
Pier Skew, UpSta & Num, DnSta & Num=  ,1663.5, 4 ,1663.5, 4 , 3 , 3 , 0 ,,
    1.35    1.35     2.3     2.3
       5   17.33   17.33   19.63
    1.35    1.35     2.3     2.3
       5   17.33   17.33   19.63
BR Coef=-1 , 0 , 0 ,, 0 ,,,0.8,0,,0,
WSPro=,,,, 1 ,,,, 0 ,,,, 0 ,,,,-1 ,-1 ,-1 , 0 , 0 , 0 , 0 , 0
BC Design=,, 0 ,, 0 ,,,,,,
BC HTab HWMax=23.81

Type RM Length L Ch R = 1 ,8229    ,46.94,47.05,47.22
BEGIN DESCRIPTION:
Copy of 452s4u - xsec 2/4 of Baker Rd.
Bank Station offset =      3349
Channel Manning's n decreased to represent concrete lining.
END DESCRIPTION:
XS GIS Cut Line= 5
     3247831.918    13849350.006     3246292.945    13849365.931
     3246102.917    13849355.696     3245369.593    13849320.211
     3244196.701    13849469.704
#Sta/Elev= 30
       0   24.07  110.73   21.88  204.64    22.9   244.4   22.02  497.62   22.86
  919.08   22.08  987.79   20.38 1354.83   20.33 1405.43   21.61 1568.95   22.54
 1626.08   22.05  1644.8   10.19 1650.57    9.43  1658.5   10.46 1678.47   22.96
 1734.53    22.2 1740.34    21.1 1772.74   21.71 1886.54   19.48 1926.07   20.84
 1958.82   20.28 2194.83   21.72 2295.11   21.12 2323.99   20.04 2354.02   21.35
 2463.54   21.65 2637.44   20.35 2874.72   21.34 2991.77   20.47 3645.92   23.69
#Mann= 6 ,-1 , 0
       0    .045       0  919.08     .99       0 1405.43    .045       0
 1626.08    .015       0 1678.47    .045       0 2194.83     .99       0
#XS Ineff= 2 , 0
       0  1618.5   20.23 1685.12       0   20.23
Permanent Ineff=
       F       F
Bank Sta=1626.08,1678.47
Exp/Cntr=0.5,0.3

Type RM Length L Ch R = 1 ,8182    ,982.01,983.1,984.45
BEGIN DESCRIPTION:
Copy of 452s4u - xsec 1/4 of Baker Rd.
Manning's n set at 0.035 in channel due to low value of 0.025 in FIS study.  Not set at 0.025 due to PMT directive regarding n values in maintained channels.
Bank Station offset =      3358
END DESCRIPTION:
XS GIS Cut Line= 5
     3247831.918     13849294.63      3246300.03    13849319.346
     3246110.002     13849309.11     3245363.007    13849272.964
     3244160.251    13849446.509
#Sta/Elev= 30
       0    24.1  125.16   22.15  488.88   23.02  539.03   21.93  680.59   22.79
  702.83   21.93  926.29   22.16  974.57   20.97 1162.32   21.29  1335.8   20.21
 1383.65   21.76 1617.92   22.01 1636.64   10.15 1642.41    9.39 1650.34   10.42
 1670.31   22.92 1768.46   21.96  1868.3   19.32 1906.63   21.04 2267.28   22.02
 2317.37   20.35 2354.15   21.54 2478.49   21.85 2710.07   21.49 2859.14   20.18
 2909.74    21.2 3001.59   20.37 3018.98   21.09 3272.87   21.15 3685.47   23.61
#Mann= 6 ,-1 , 0
       0    .045       0  926.29     .99       0 1383.65    .045       0
 1617.92    .035       0 1670.31    .045       0 2267.28     .99       0
Bank Sta=1617.92,1670.31
Exp/Cntr=0.3,0.1

Type RM Length L Ch R = 1 ,7199    ,1091.99,1090.73,1091.29
BEGIN DESCRIPTION:
452v7
Manning's n set at 0.035 in channel due to low value of 0.025 in FIS study.  Not set at 0.025 due to PMT directive regarding n values in maintained channels.
Bank Station offset =      3589
END DESCRIPTION:
XS GIS Cut Line= 4
     3247818.074    13848602.426      3246486.84    13848372.474
     3246367.535    13848359.233      3245256.92    13848297.857
#Sta/Elev= 30
       0   23.86  110.52   24.07  250.97   22.07  278.38   22.87  405.95   22.96
  599.44   21.37  621.49   17.81  648.48   15.56  664.47    17.5  693.08   19.15
  712.83   21.33  752.68   22.73  802.49   21.64  825.16   22.67  938.03   22.63
 1063.64   21.41 1343.74   21.73 1366.56   20.76 1402.53     8.2 1404.36    9.24
 1410.83    6.28 1414.37    7.04 1434.61   17.24 1451.93   23.34 1555.99   22.37
 1606.65   19.27 1699.89   22.03 2369.93   21.86 2511.12   22.91  2583.3   24.26
#Mann= 7 ,-1 , 0
       0    .045       0  599.44     .99       0  712.83    .045       0
 1366.56    .035       0 1451.93    .045       0 1555.99     .99       0
 1699.89    .045       0
Bank Sta=1366.56,1451.93
Exp/Cntr=0.3,0.1

Type RM Length L Ch R = 1 ,6108    ,831.65,824.76,816.84
BEGIN DESCRIPTION:
452v6
Manning's n set at 0.035 in channel due to low value of 0.025 in FIS study.  Not set at 0.025 due to PMT directive regarding n values in maintained channels.
Bank Station offset =      3987
END DESCRIPTION:
XS GIS Cut Line= 4
     3247651.945    13847432.602     3246695.596    13847305.741
     3246589.944    13847294.973     3246005.467    13847245.453
#Sta/Elev= 30
       0   23.85   87.17   22.75  268.34   22.66   315.7   21.02  421.62   21.65
  670.25   21.47   803.5   20.58  830.17   19.52  875.56    22.6  958.68   22.41
  966.28   21.16  974.61   21.08  995.62    11.9 1007.15    5.85 1012.63    5.53
 1017.45    5.79  1027.7    9.23 1059.61   21.31 1064.37   21.51 1069.33    20.9
 1077.72   22.18 1169.65   21.64 1207.37   18.43 1227.93   18.36 1240.32   18.39
 1284.49    21.7  1297.7   22.12  1311.7   21.49 1358.61   22.27  1657.5   21.96
#Mann= 4 ,-1 , 0
       0    .045       0  974.61    .035       0 1059.61    .045       0
 1169.65     .99       0
Bank Sta=974.61,1059.61
Exp/Cntr=0.3,0.1

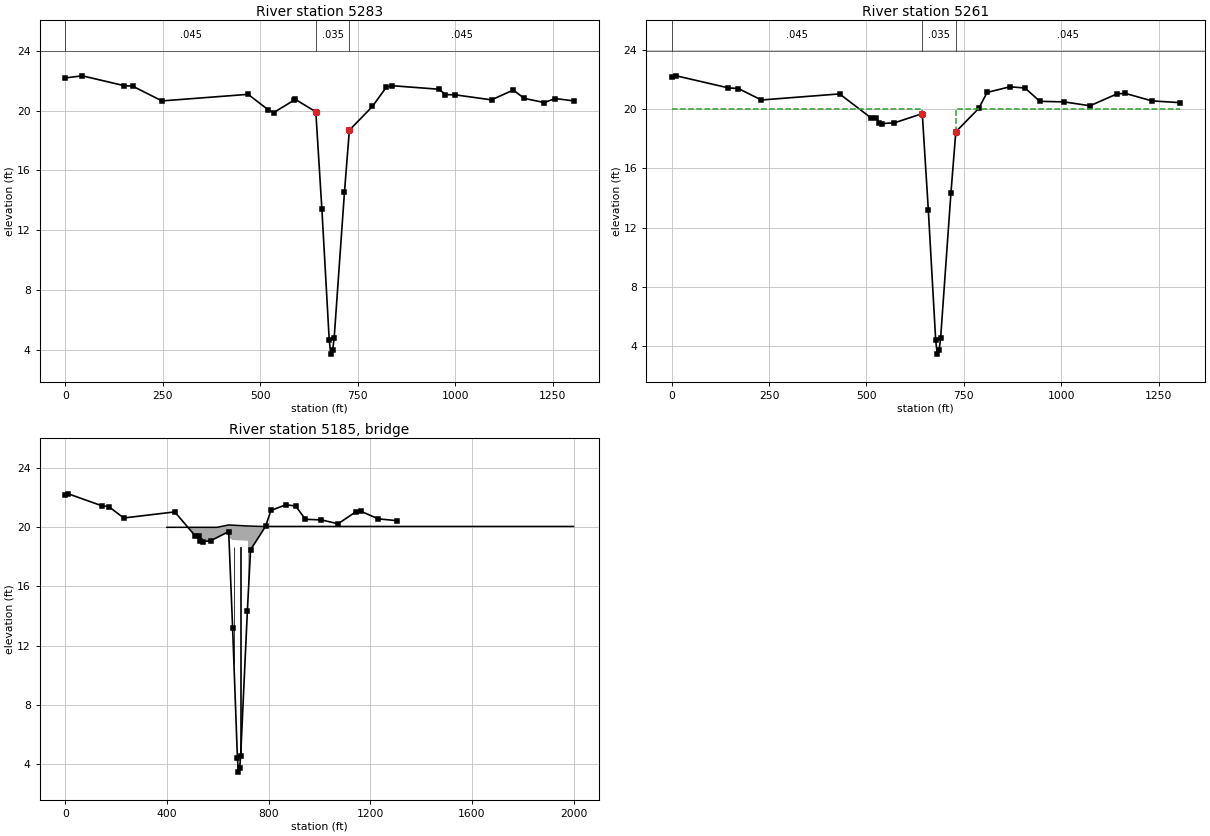
Type RM Length L Ch R = 1 ,5283    ,22.47,22.46,22.44
BEGIN DESCRIPTION:
452s3u - xsec 4/4 Rolling Brook Rd.
Manning's n set at 0.035 in channel due to low value of 0.025 in FIS study.  Not set at 0.025 due to PMT directive regarding n values in maintained channels.
Bank Station offset =      4319
END DESCRIPTION:
XS GIS Cut Line= 4
     3247384.178    13846515.246      3246774.01    13846473.799
     3246606.142    13846487.276      3246083.15    13846460.223
#Sta/Elev= 30
       0    22.2   43.96   22.34  151.36   21.68   172.8   21.65  248.13   20.66
  469.07    21.1  520.47   20.07  534.82   19.88  585.72   20.69  588.37   20.79
  642.71   19.93  658.29    13.4  677.15    4.63  681.15     3.7  685.99    3.98
  689.82    4.79  716.22   14.56  728.77    18.7  787.88   20.29  823.61   21.58
  837.76   21.68  959.28   21.44  974.91   21.08   999.4   21.07 1093.48   20.73
 1149.23   21.39 1177.23   20.83 1228.51   20.55 1257.03   20.82 1303.67   20.66
#Mann= 3 , 0 , 0
       0    .045       0  642.71    .035       0  728.77    .045       0
Bank Sta=642.71,728.77
Exp/Cntr=0.5,0.3

Type RM Length L Ch R = 1 ,5261    ,151.06,151.86,153.05
BEGIN DESCRIPTION:
Copy of 452s3u - xsec 3/4 Rolling Brook Rd.
Manning's n set at 0.035 in channel due to low value of 0.025 in FIS study.  Not set at 0.025 due to PMT directive regarding n values in maintained channels.
Bank Station offset =      4318
END DESCRIPTION:
XS GIS Cut Line= 4
     3247381.006    13846493.037     3246770.837     13846451.59
      3246602.97    13846465.067     3246079.451    13846430.635
#Sta/Elev= 30
       0   22.19   12.08   22.25  144.82   21.44  171.32   21.39  230.22   20.62
  430.92   21.03  512.22    19.4  525.62   19.41  530.96    19.1  540.67   19.03
  571.88   19.08  643.18    19.7  658.76   13.17  677.62     4.4  681.62    3.47
  686.46    3.75  690.29    4.56  716.69   14.33  729.24   18.47  788.35   20.06
   809.5   21.13  868.04   21.51  906.55   21.43  945.03   20.53 1007.48   20.49
 1073.66   20.23 1142.86   21.03 1163.56   21.07 1232.31   20.56 1304.63   20.44
#Mann= 3 , 0 , 0
       0    .045       0  643.18    .035       0  729.24    .045       0
#XS Ineff= 2 , 0
       0  643.18   19.99  729.24       0   19.99
Permanent Ineff=
       F       F
Bank Sta=643.18,729.24
Exp/Cntr=0.5,0.3

Type RM Length L Ch R = 3 ,5185    ,,,
BEGIN DESCRIPTION:
452s3 - Rolling Brook Rd. (conc bridge)
and 452s2; divided highway, single structure modeled although small area (3.5') open between
2-33' roadway bridge crossings; u/s roadway elevations used
END DESCRIPTION:
Bridge Culvert--1,0,-1,-1, 0
Deck Dist Width WeirC Skew NumUp NumDn MinLoCord MaxHiCord MaxSubmerge Is_Ogee
41,70,2.6,0, 9, 9, , , 0.95, 0, 0,0,,
     400  596.71   643.3  644.12  717.75  719.12  769.64     782    2000
   19.99   19.99   20.15   20.15   20.08   20.08   20.05   20.05   20.05
                           19.15   19.08   19.08
     550  609.71     648   649.5   656.3   724.5  730.75  782.64     795
   19.99   19.99   20.15   20.15   20.15   20.15   20.08   20.05   20.05
                           19.15   19.15   19.15
Pier Skew, UpSta & Num, DnSta & Num=  ,664, 4 ,669.38, 4 , 3 , 3 , 0 ,,
    1.35    1.35       2       2
       0    16.6    16.6   18.65
    1.35    1.35       2       2
       0    16.6    16.6   18.65
Pier Skew, UpSta & Num, DnSta & Num=  ,690.1, 4 ,695.48, 4 , 3 , 3 , 0 ,,
    1.35    1.35       2       2
       0    16.6    16.6   18.65
    1.35    1.35       2       2
       0    16.6    16.6   18.65
BR Coef=-1 , 0 , 0 ,, 0 ,,,0.8,-1,,0,
WSPro=,,,, 1 ,,,, 0 ,,,, 0 ,,,,-1 ,-1 ,-1 , 0 , 0 , 0 , 0 , 0
BC Design=,, 0 ,, 0 ,,,,,,
BC HTab HWMax=22.25