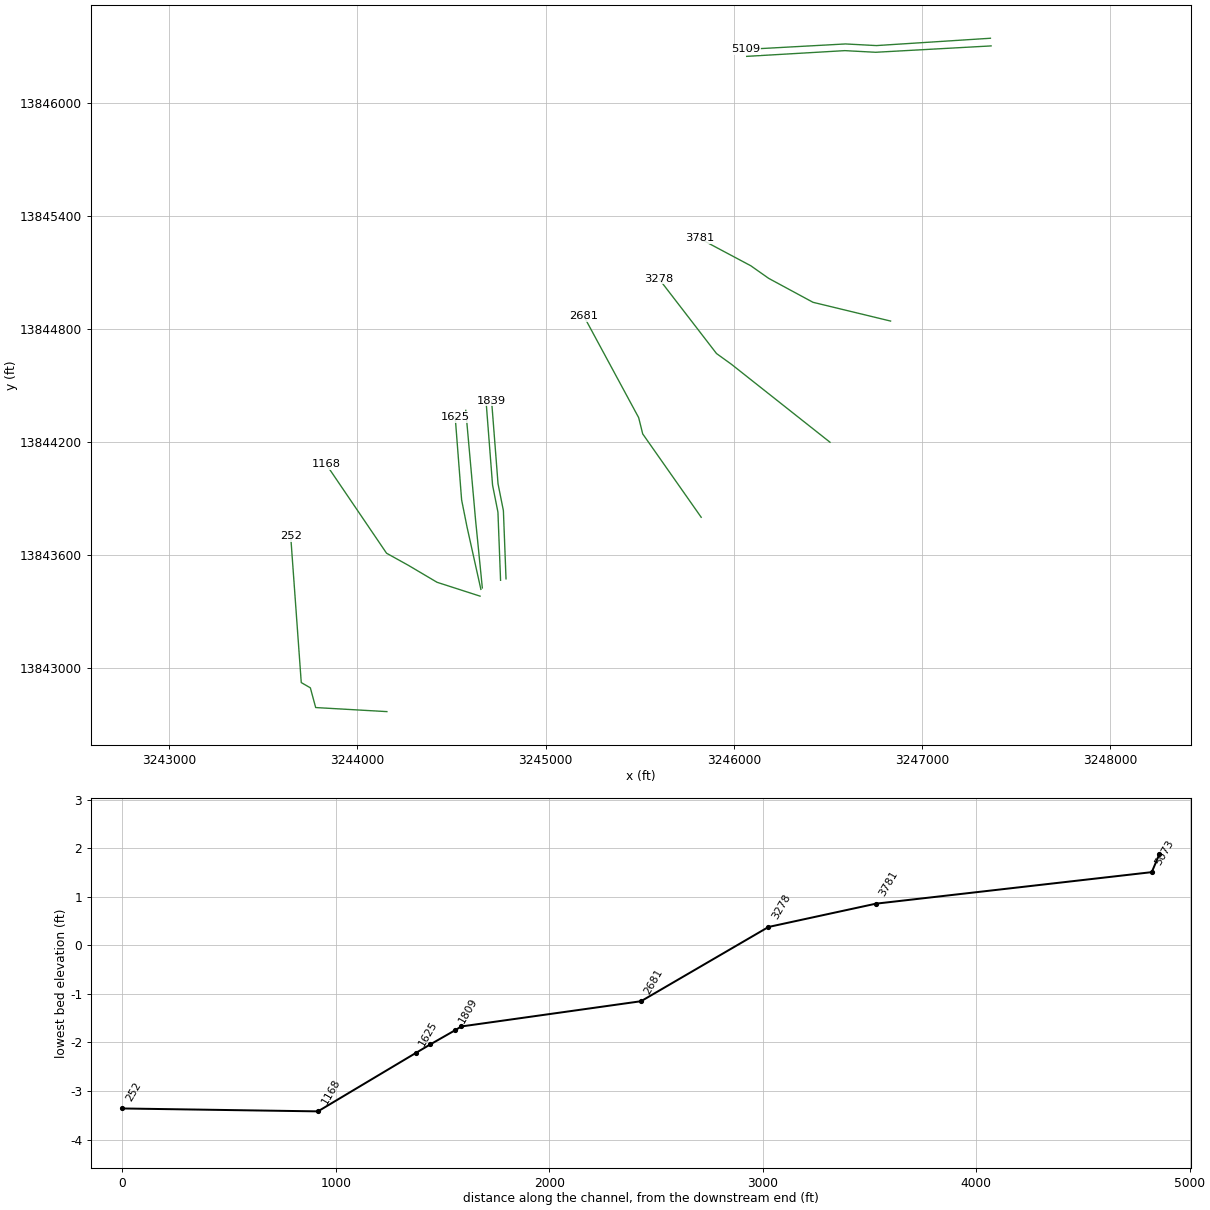
HEC-RAS study O105-00-00.prj: O105-00-00

--- O105-00-00.g02 (geometry) --- (continued)

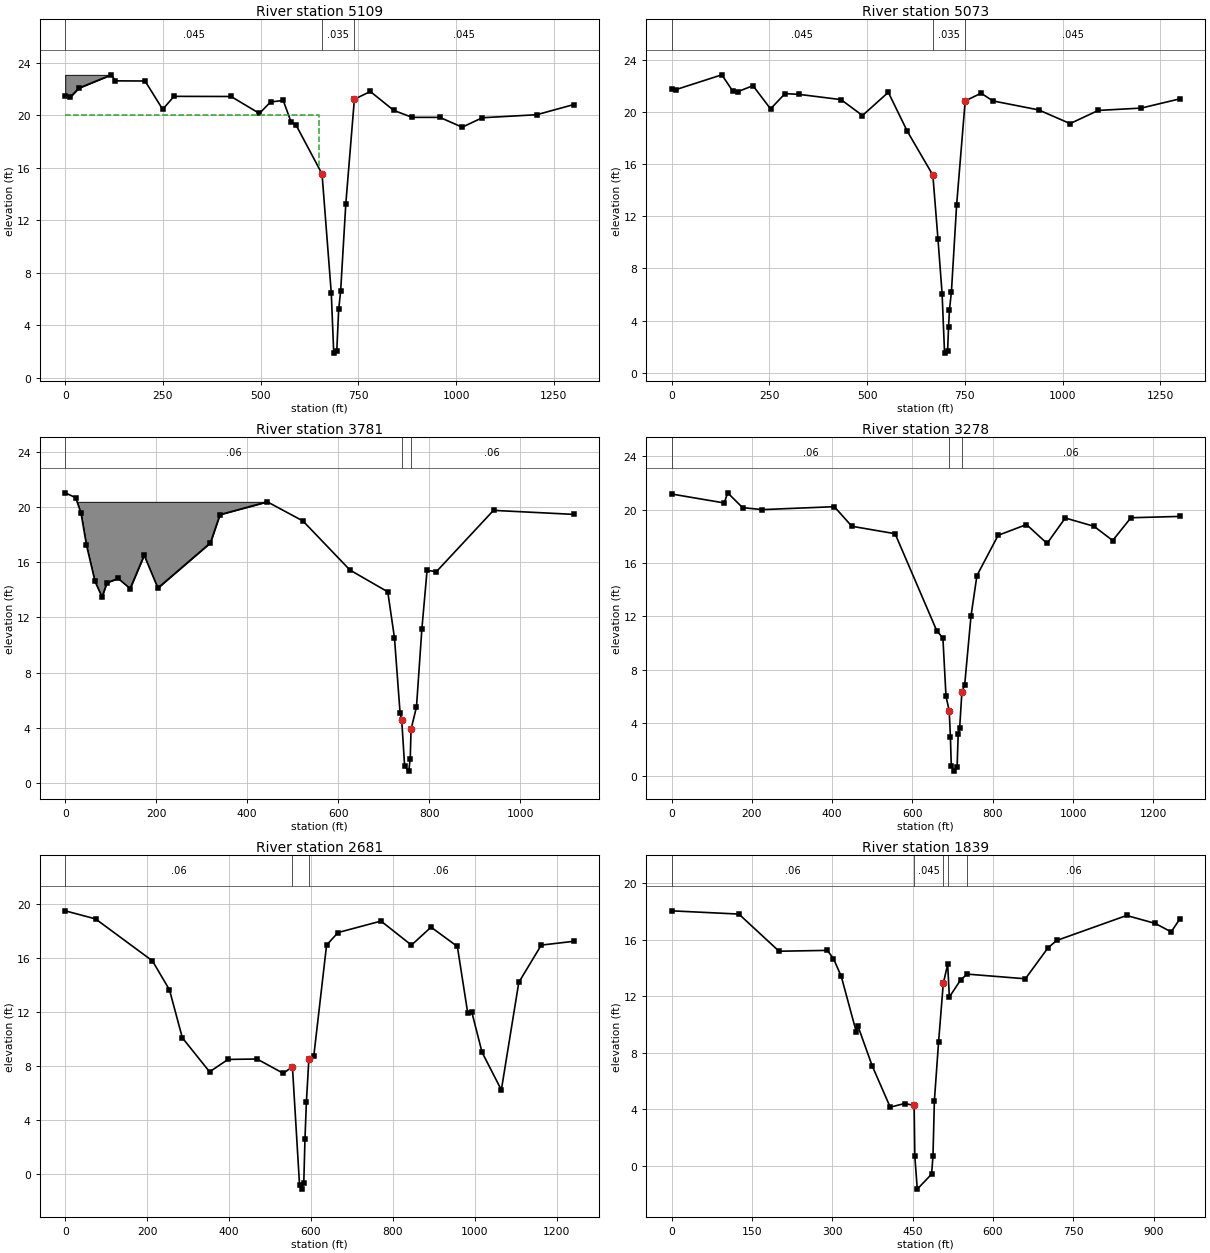
Type RM Length L Ch R = 1 ,5109    ,35.77,35.8,35.85
BEGIN DESCRIPTION:
452s2d - xsec 2/4 Rolling Brook Rd.
Manning's n set at 0.035 in channel due to low value of 0.025 in FIS study.  Not set at 0.025 due to PMT directive regarding n values in maintained channels.
Bank Station offset =      4313
END DESCRIPTION:
XS GIS Cut Line= 4
     3247362.832    13846341.871     3246757.216    13846302.935
      3246593.52    13846311.653     3246064.657    13846282.695
#Sta/Elev= 30
       0   21.49    13.1   21.39   35.06   22.07  117.91   23.08  128.25   22.62
  204.27   22.61  249.36   20.45  278.33   21.44  424.24   21.43  496.82   20.14
  525.35   21.01  557.77   21.13   577.5   19.51  590.27   19.27  657.04   15.53
  680.69    6.45     687    1.88   694.8    2.07   699.6    5.21  704.58    6.59
  717.91   13.27  739.78   21.22  780.53   21.81  840.56   20.37   887.6   19.84
  958.41   19.84  1015.7   19.09 1066.73   19.81 1206.14   20.04 1300.45   20.81
#Mann= 3 , 0 , 0
       0    .045       0  657.04    .035       0  739.78    .045       0
#XS Ineff= 2 , 0
       0     648   19.99  742.79       0   19.99
Permanent Ineff=
       F       F
#Block Obstruct= 2 , 0
       0  117.91   23.08               0
Bank Sta=657.04,739.78
Exp/Cntr=0.5,0.3

Type RM Length L Ch R = 1 ,5073    ,1316.5,1292.3,1267.26
BEGIN DESCRIPTION:
Copy of 452s2d - xsec 1/4 Rolling Brrok Rd.
Manning's n set at 0.035 in channel due to low value of 0.025 in FIS study.  Not set at 0.025 due to PMT directive regarding n values in maintained channels.
Bank Station offset =      4302
END DESCRIPTION:
XS GIS Cut Line= 4
     3247366.531    13846301.187     3246753.409    13846267.401
     3246589.712    13846276.118     3246068.356     13846245.71
#Sta/Elev= 30
       0   21.77   11.12   21.72  128.25   22.85  156.56   21.59  168.63   21.55
  207.86   22.02  252.93   20.24  290.01   21.41  325.93   21.35  433.08   20.95
  488.04   19.73  554.09   21.51  602.92   18.51  668.04   15.16  681.17   10.25
  691.69    6.08     698    1.51   705.8     1.7  708.24    3.54   710.6    4.84
  715.58    6.22  728.91    12.9  750.78   20.85  791.53   21.44  821.55   20.85
  938.69   20.16 1019.12   19.11 1091.08   20.12 1201.02    20.3 1300.22   21.01
#Mann= 3 , 0 , 0
       0    .045       0  668.04    .035       0  750.78    .045       0
Bank Sta=668.04,750.78
Exp/Cntr=0.3,0.1

Type RM Length L Ch R = 1 ,3781    ,503.29,502.99,508.76
BEGIN DESCRIPTION:
452v5
Bank Station offset =      4245
left overbank blocked, includes subdivision area where flow
is not part of stream conveyance system
END DESCRIPTION:
XS GIS Cut Line= 5
     3246832.694    13844840.366       3246420.5    13844940.017
     3246185.389    13845066.992     3246089.857    13845134.169
     3245816.532    13845279.512
#Sta/Elev= 30
       0   21.01    22.9   20.66   34.68   19.55   46.72   17.23   65.55   14.59
   80.98   13.47   91.59    14.5  116.44   14.81  142.71   14.08  173.57   16.49
  203.72   14.12  319.24   17.39  340.14   19.43   444.3   20.36  522.77   18.97
  626.05   15.42  709.22   13.84  723.92   10.51  736.34    5.04  739.87    4.57
   746.3    1.21  755.34     .86  758.64    1.77  760.35    3.89  772.34    5.51
  784.13   11.13   795.6    15.4  816.02    15.3   941.7   19.74 1117.63   19.45
#Mann= 3 , 0 , 0
       0     .06       0  739.87    .045       0  760.35     .06       0
#Block Obstruct= 2 , 0
       0   444.3   20.36               0
Bank Sta=739.87,760.35
Exp/Cntr=0.3,0.1

Type RM Length L Ch R = 1 ,3278    ,633.91,596.99,567
BEGIN DESCRIPTION:
452v4
Bank Station offset =      4297
END DESCRIPTION:
XS GIS Cut Line= 4
     3246510.994    13844196.968     3245986.962     13844611.21
     3245908.076    13844667.932     3245602.066    13845065.045
#Sta/Elev= 30
       0   21.18  130.84   20.51  139.54   21.27  176.55   20.16  225.64   20.01
  405.23   20.23  448.87   18.76   556.7    18.2  660.58   10.91  675.76   10.37
  683.49       6   691.5     4.9   694.5    2.93  696.62     .79  703.39     .38
  711.13     .68  713.87    3.16  717.55    3.63  723.04    6.29  730.06    6.87
   745.8   12.03  760.57   15.06  813.39   18.08  883.97   18.89  935.28   17.47
  980.59   19.38  1052.1   18.76 1098.77   17.69 1144.18    19.4 1266.49    19.5
#Mann= 3 , 0 , 0
       0     .06       0   691.5    .045       0  723.04     .06       0
Bank Sta=691.5,723.04
Exp/Cntr=0.3,0.1

Type RM Length L Ch R = 1 ,2681    ,859.29,841.6,853.49
BEGIN DESCRIPTION:
452v3
Bank Station offset =      4422
END DESCRIPTION:
XS GIS Cut Line= 4
     3245826.745    13843798.673     3245516.064    13844241.347
     3245494.738     13844327.48     3245203.771    13844865.898
#Sta/Elev= 30
       0   19.47   74.15   18.87  213.08   15.76   254.6   13.62  286.13   10.06
  352.68    7.54  397.64    8.46  468.55    8.49  532.74    7.43  554.98    7.92
  572.27    -.81   577.6   -1.15  582.73    -.66  585.63    2.59  589.11    5.32
  595.13    8.49  607.09     8.7  638.39   16.93   666.3   17.86  771.32   18.71
  845.66   16.93  893.57   18.26  957.81   16.83  983.11    11.9  992.97   11.98
 1018.07    8.99 1065.26     6.2  1107.9   14.17 1162.72   16.93 1241.56   17.21
#Mann= 3 , 0 , 0
       0     .06       0  554.98    .045       0  595.13     .06       0
#Block Obstruct= 2 , 0
       0                  957.81       0   16.83
Bank Sta=554.98,595.13
Exp/Cntr=0.3,0.1

Type RM Length L Ch R = 1 ,1839    ,29.97,30.03,30.31
BEGIN DESCRIPTION:
452s1u - xs 4/4 of Garth Rd.
Bank Station offset =      4541
END DESCRIPTION:
XS GIS Cut Line= 4
     3244790.158    13843471.867     3244776.165    13843833.933
     3244747.666     13843976.79     3244713.563     13844416.54
#Sta/Elev= 30
       0   18.03  125.47    17.8  200.48   15.17  290.55   15.23  302.06   14.65
  316.62   13.39  344.52    9.48   347.6    9.89  374.36    7.06  408.04    4.13
  434.84    4.39  452.71    4.26  453.98     .65  458.56   -1.67  485.28    -.61
  487.88     .67  490.49    4.59  498.39    8.77   507.1   12.89  515.32   14.24
  518.45   11.93  539.76   13.15  551.73   13.55  660.36   13.22  702.63   15.41
  718.78   15.93  849.44    17.7  902.72   17.14  932.61   16.54  949.08   17.47
#Mann= 5 ,-1 , 0
       0     .06       0  452.71    .045       0   507.1     .06       0
  515.32     .99       0  551.73     .06       0
Bank Sta=452.71,507.1
Exp/Cntr=0.5,0.3

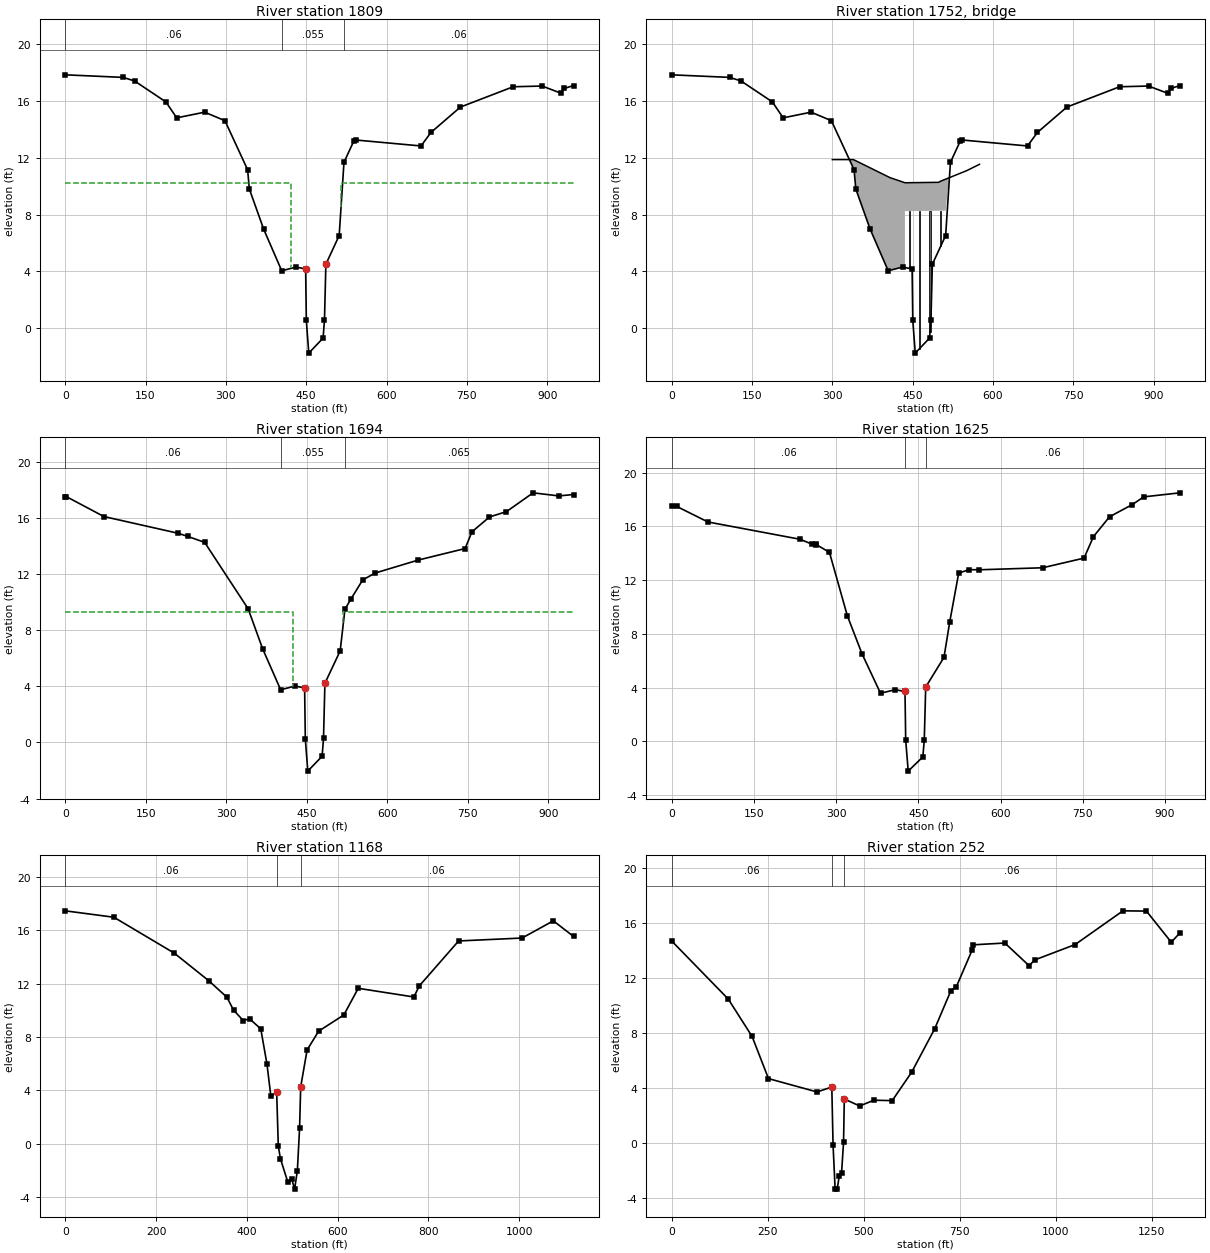
Type RM Length L Ch R = 1 ,1809    ,120.87,115.39,111
BEGIN DESCRIPTION:
Copy of 452s1u.  - xs 3/4 of Garth Rd.
deleted rob surveyed high pt as this is a copy of u/s section and it went through the road (#494.59 & 503.3)
Bank Station offset =      4545
Mannings "n" to reflect channel widened to incorporate entire bridge opening, channel 'n' raised to reduce negative change in profile
END DESCRIPTION:
XS GIS Cut Line= 4
     3244761.161    13843464.192     3244747.168    13843826.258
      3244718.67    13843969.115     3244684.566    13844408.865
#Sta/Elev= 30
       0   17.85   108.1   17.67  129.38   17.42  188.06   15.94  208.16   14.82
  260.32   15.22  298.23   14.62  340.52   11.17   343.8    9.81  370.56    6.98
  404.24    4.05  431.04    4.31  448.91    4.18  450.18     .57  454.76   -1.75
  481.48    -.69  484.08     .59  486.69    4.51  511.52    6.53  520.49   11.69
  538.89   13.19  542.41   13.26  664.38   12.84  682.79   13.79  737.94   15.58
  836.37   17.01  890.41   17.06  926.03   16.55  931.48   16.89  949.08   17.09
#Mann= 3 ,-1 , 0
       0     .06       0  404.24    .055       0  520.49     .06       0
#XS Ineff= 2 , 0
       0  421.86   10.25     515       0   10.25
Permanent Ineff=
       F       F
Bank Sta=448.91,486.69
Exp/Cntr=0.5,0.3

Type RM Length L Ch R = 3 ,1752    ,,,
BEGIN DESCRIPTION:
452s1u - Garth Rd. (conc Bridge)
END DESCRIPTION:
Bridge Culvert--1,0,-1,-1, 0
Deck Dist Width WeirC Skew NumUp NumDn MinLoCord MaxHiCord MaxSubmerge Is_Ogee
20.58,73.84,2.6,0, 9, 9, , , 0.95, 0, 0,0,,
     300  339.37  407.58   435.5   438.5   498.8   501.5  550.82  574.83
   11.88   11.88   10.61   10.25   10.25   10.28   10.35    11.1   11.55
                            8.25    8.25    8.28    8.28    8.25
     300  340.87  410.58   438.5   441.5   501.5   504.5  553.82  577.83
   11.88   11.88   10.61   10.28   10.25   10.28   10.35    11.1   11.55
                            8.25    8.25    8.28    8.28    8.28
Pier Skew, UpSta & Num, DnSta & Num=  ,443.17, 4 ,440.16, 4 , 3 , 3 , 0 ,,
    1.35    1.35       2       2
      -5    6.25    6.25    9.88
    1.35    1.35       2       2
      -5    6.25    6.25    9.88
Pier Skew, UpSta & Num, DnSta & Num=  ,462.35, 4 ,459.34, 4 , 3 , 3 , 0 ,,
    1.35    1.35       2       2
      -5    6.25    6.25    9.88
    1.35    1.35       2       2
      -5    6.25    6.25    9.88
Pier Skew, UpSta & Num, DnSta & Num=  ,482.35, 4 ,479.34, 4 , 3 , 3 , 0 ,,
    1.35    1.35       2       2
      -5    6.25    6.25    9.88
    1.35    1.35       2       2
      -5    6.25    6.25    9.88
Pier Skew, UpSta & Num, DnSta & Num=  ,502.12, 4 ,499.11, 4 , 3 , 3 , 0 ,,
    1.35    1.35       2       2
      -5    6.25    6.25    9.88
    1.35    1.35       2       2
      -5    6.25    6.25    9.88
BR Coef=-1 , 0 , 0 ,, 0 ,,,0.8,0,,0,
WSPro=,,,, 1 ,,,, 0 ,,,, 0 ,,,,-1 ,-1 ,-1 , 0 , 0 , 0 , 0 , 0
BC Design=,, 0 ,, 0 ,,,,,,
BC HTab HWMax=17.85

Type RM Length L Ch R = 1 ,1694    ,68.74,69.24,67.88
BEGIN DESCRIPTION:
Copy of 452s1u. - xs 2/4 of Garth Rd.
deleted rob surveyed high pt as this is a copy of u/s section and it went through the road (#491.48, 500.29 & 508.51)
Bank Station offset =      4548
Mannings "n" to reflect channel widened to incorporate entire bridge opening, channel 'n' raised to reduce negative change in profile
END DESCRIPTION:
XS GIS Cut Line= 4
     3244664.316    13843423.628     3244628.383    13843783.908
     3244615.629    13843928.035     3244576.257    13844366.223
#Sta/Elev= 29
       0   17.52    2.09   17.52    72.1    16.1  210.21   14.91  227.88   14.69
  259.71   14.26  340.79    9.52  367.55    6.69  401.23    3.76  428.03    4.02
   445.9    3.89  447.17     .28  451.75   -2.04  478.47    -.98  481.07      .3
  483.68    4.22  512.11    6.53  520.98    9.49   531.6   10.19  554.01   11.58
  576.83   12.07  657.52      13  744.78   13.82  757.45   15.01   790.2   16.07
   821.8   16.45   871.4   17.79  919.32   17.57  946.71   17.67
#Mann= 3 ,-1 , 0
       0     .06       0  401.23    .055       0  520.98    .065       0
#XS Ineff= 2 , 0
       0  424.05    9.27     518       0    9.27
Permanent Ineff=
       F       F
Bank Sta=445.9,483.68
Exp/Cntr=0.5,0.3

Type RM Length L Ch R = 1 ,1625    ,410.96,457.07,502.49
BEGIN DESCRIPTION:
Copy of 452s1u. - xs 1/4 of Garth Rd.
deleted rob surveyed high pt as this is a copy of u/s section and it went through the road (#471.3, 480.01 & 488.23)
Bank Station offset =      4569
END DESCRIPTION:
XS GIS Cut Line= 4
     3244656.579    13843415.892     3244582.763    13843748.319
     3244554.264    13843891.176     3244520.161    13844330.926
#Sta/Elev= 30
       0   17.49    9.08   17.49   66.14   16.33  234.45   15.04  255.84   14.68
  262.55   14.66  263.64   14.65   287.8   14.07  320.51    9.34  347.27    6.51
  380.95    3.58  407.75    3.84  425.62    3.71  426.89      .1  431.47   -2.22
  458.19   -1.16  460.79     .12   463.4    4.04  496.72    6.25  507.28     8.9
  523.53   12.52  542.23   12.78  560.94   12.77  676.68   12.92  752.26   13.64
  769.36   15.24   798.8   16.72  840.03   17.62  861.25    18.2  927.27    18.5
#Mann= 3 , 0 , 0
       0     .06       0  425.62    .045       0   463.4     .06       0
Bank Sta=425.62,463.4
Exp/Cntr=0.3,0.1

Type RM Length L Ch R = 1 ,1168    ,886.41,915.9,797.59
BEGIN DESCRIPTION:
452v2
Bank Station offset =      4495
END DESCRIPTION:
XS GIS Cut Line= 5
     3244652.287    13843379.953     3244423.744    13843453.544
     3244270.367    13843544.207     3244155.642    13843607.805
     3243835.272    13844079.522
#Sta/Elev= 30
       0   17.45  107.13   16.97   240.1   14.28  315.75   12.22  355.98   10.98
  370.89      10  392.23    9.22  406.15    9.35  430.77     8.6  444.38    5.96
  453.01    3.54  465.78    3.85  469.35    -.18  473.95   -1.13  490.31   -2.89
   499.1   -2.67   505.3   -3.42  511.36   -2.03  516.21    1.13  518.68    4.25
  532.83    7.02  558.37    8.43  613.72    9.64  645.41   11.64  767.92   10.99
  780.19   11.83  866.53   15.19 1006.31   15.41 1075.19    16.7 1119.66   15.53
#Mann= 3 , 0 , 0
       0     .06       0  465.78    .045       0  518.68     .06       0
Bank Sta=465.78,518.68
Exp/Cntr=0.3,0.1

Type RM Length L Ch R = 1 ,252     ,281.77,251.73,356.66
BEGIN DESCRIPTION:
452v1
Bank Station offset =      4575
ROB and LOB reach lengths > channel Reach length due to
confluence with Goose Creek
END DESCRIPTION:
XS GIS Cut Line= 6
     3244157.339    13842766.904     3243779.189    13842788.458
     3243760.789    13842856.448     3243750.976    13842893.071
     3243702.612    13842921.108     3243646.446    13843699.289
#Sta/Elev= 30
       0   14.67  147.27   10.45  209.39    7.73  251.95    4.67  378.53     3.7
  416.82    4.06  420.13    -.17   425.5   -3.36  430.87   -3.36  436.31   -2.39
  442.23   -2.18  447.41     .03  449.37    3.19  489.43    2.68  526.13     3.1
  574.13    3.07  624.78    5.14  684.66    8.29   726.9   11.06  741.12   11.35
   782.6   14.04  784.73   14.39  867.31   14.52  930.51   12.87  944.85   13.29
 1050.27   14.41 1174.74   16.86 1235.91   16.84 1300.48   14.58 1323.22   15.26
#Mann= 3 , 0 , 0
       0     .06       0  416.82    .045       0  449.37     .06       0
Bank Sta=416.82,449.37
Exp/Cntr=0.3,0.1

Chan Stop Cuts=-1
Use User Specified Reach Order=0
User Specified Reach Order=O105-00-00      ,O105-00-00_0003